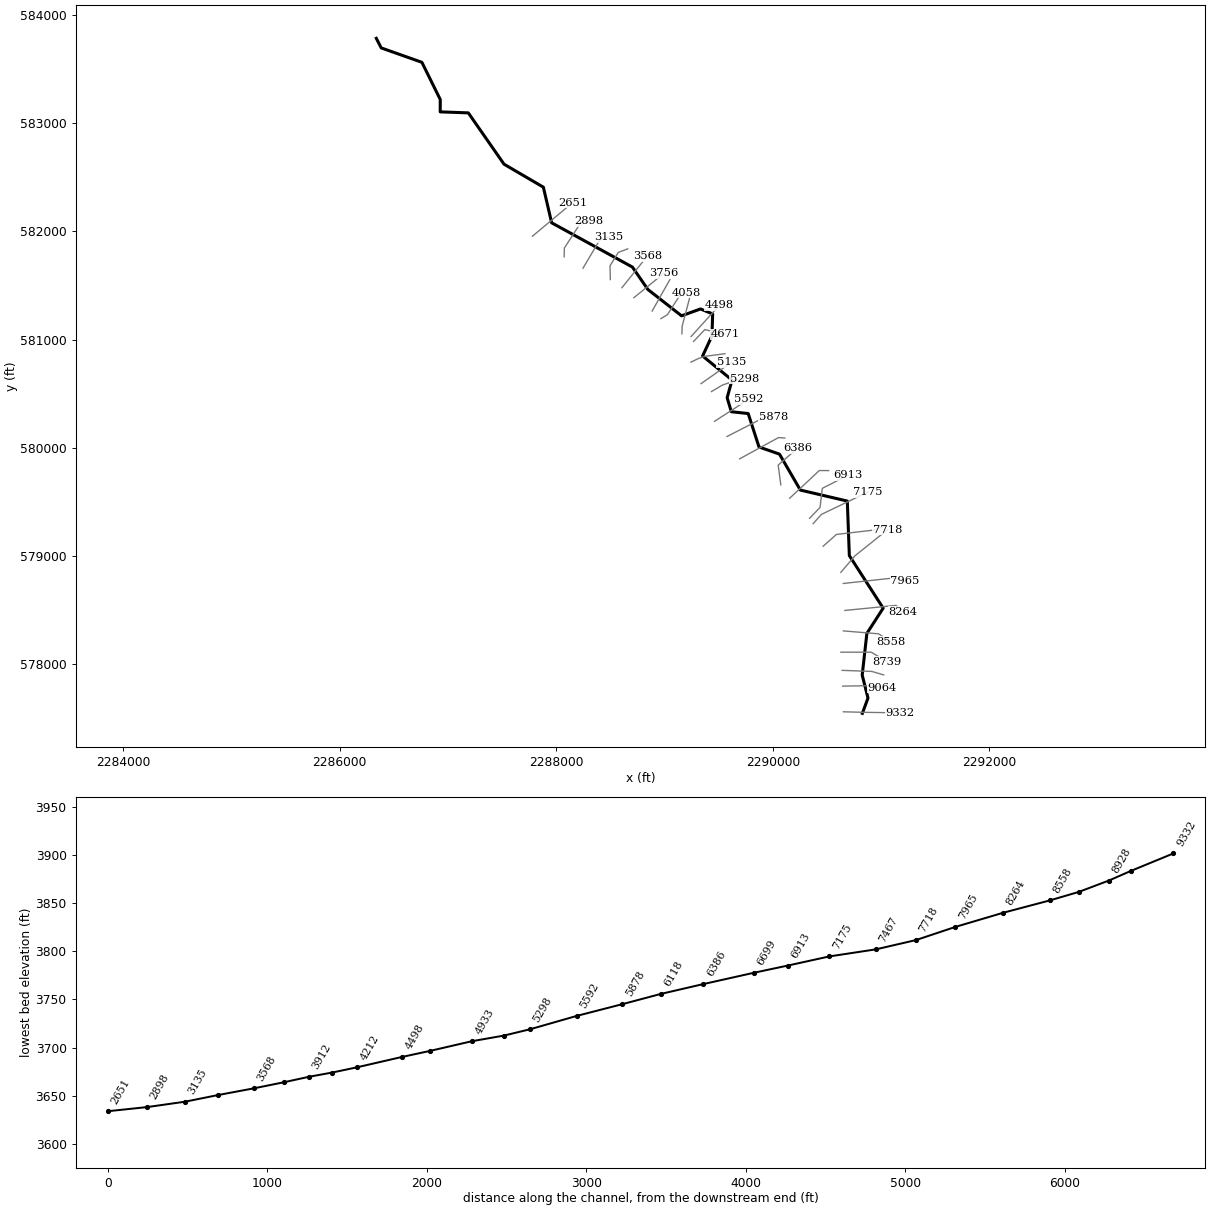
--- FISHHTCHRN.prj (project) ---

Proj Title=FISHHTCHRN
Current Plan=p01
Default Exp/Contr=0,0
English Units
Geom File=g01
Flow File=f01
Plan File=p01
BEGIN DESCRIPTION:
----------MODEL BY WOOD PLC 2022----------
AFH study
Randolph County, WV
HEC-RAS Version: RAS 6.2
Vertical Datum: NAVD88
Projection: NAD 1983 StatePlane West Virginia S FIPS 4702 (US Feet)
Terrain: 1-meter LIDAR (FEMA Region III 3DEP collected 2016-2018)
Land Use: 2019 NLCD
Hydrologic Method:
WV SIR2010-5033 regression equations
Additional Model Notes:
None
END DESCRIPTION:
DSS Export Rating Curves= 0
DSS Export Rating Curve Sorted= 0
DSS Export Volume Flow Curves= 0
DXF OffsetX= 0
DXF OffsetY= 0
DXF ScaleX= 0
DXF ScaleY= 0

--- FISHHTCHRN.p01 (plan) ---

Plan Title=Floodplain
Program Version=6.20
Short Identifier=Floodplain
Geom File=g01
Flow File=f01
Subcritical Flow
K Sum by GR= 0
Std Step Tol= 0.01
Critical Tol= 0.01
Num of Std Step Trials= 20
Max Error Tol= 0.3
Flow Tol Ratio= 0.001
Split Flow NTrial= 30
Split Flow Tol= 0.02
Split Flow Ratio= 0.02
Log Output Level= 0
Friction Slope Method= 1
Unsteady Friction Slope Method= 2
Unsteady Bridges Friction Slope Method= 1
Parabolic Critical Depth
Global Vel Dist= 0 , 0 , 0
Global Log Level= 0
CheckData=True
Encroach Param=-1 ,0,0, 0
Mapping Interval=1HOUR
Computation Time Step Use Courant=        0
Computation Time Step Use Time Series=    0
Computation Time Step Count To Double=0
Computation Time Step Max Doubling=0
Computation Time Step Max Halving=0
Computation Time Step Residence Courant=0
Run HTab= 0
Run UNet= 0
Run Sediment= 0
Run PostProcess= 0
Run WQNet= 0
Run RASMapper=-1
UNET Theta= 0
UNET Theta Warmup= 0
UNET ZTol= 0
UNET ZSATol= 0
UNET MxIter= 0
UNET Max Iter WO Improvement= 0
UNET MaxInSteps= 0
UNET DtIC= 0
UNET DtMin= 0
UNET MaxCRTS= 0
UNET WFStab= 0
UNET SFStab= 0
UNET WFX= 1
UNET SFX= 1
UNET Gravity=32.174
UNET 1D Methodology=Finite Difference
UNET DSS MLevel= 1
UNET Pardiso=0
UNET DZMax Abort= 0
UNET Use Existing IB Tables= 0
UNET Froude Reduction=False
UNET Froude Limit= 0
UNET Froude Power= 0
UNET D1 Cores= 0
UNET WindReference=Eulerian
UNET WindDragFormulation=Hsu (1988)
UNET D2 Coriolis=0
UNET D2 Cores= 0
UNET D2 Theta= 1
UNET D2 Theta Warmup= 1
UNET D2 Z Tol= 0.01
UNET D2 Volume Tol= 0.01
UNET D2 Max Iterations= 20
UNET D2 Equation= 0
UNET D2 RampUpFraction=0.1
UNET D2 TimeSlices= 1
UNET D2 Turbulence Formulation=Non-Conservative (original)
UNET D2 Eddy Viscosity=0.3
UNET D2 Transverse Eddy Viscosity=0.1
UNET D2 Smagorinsky Mixing=0
UNET D2 BCVolumeCheck=0
UNET D2 Cores=0
UNET D2 SolverType=PARDISO (Direct)
UNET D2 Minimum Iterations= 2147483647
UNET D2 Maximum Iterations= 2147483647
UNET D2 Restart Number= 10
UNET D2 Relaxation Coeff=1.3
UNET D2 SOR Precondition Iterations= 10
UNET D2 ILUT Maximum Fill= 8
UNET D2 ILUT Tolerance=1E-08
UNET D1D2 MaxIter= 0
UNET D1D2 ZTol=0.01
UNET D1D2 QTol=0.1
UNET D1D2 MinQTol=1
Write IC File= 0
Write IC File at Fixed DateTime=0
Write IC File at Sim End=0
Echo Input=False
Echo Parameters=False
Echo Output=False
Write Detailed= 0
HDF Write Warmup=0
HDF Write Time Slices=0
HDF Flush=0
HDF Compression= 1
HDF Chunk Size= 1
HDF Spatial Parts= 1
HDF Use Max Rows=0
HDF Fixed Rows= 1
Calibration Method= 0
Calibration Iterations= 20
Calibration Max Change=0.05
Calibration Tolerance=0.2
Calibration Maximum=1.5
Calibration Minimum=0.5
Calibration Optimization Method= 1
WQ AD Non Conservative
WQ ULTIMATE=-1
WQ Max Comp Step=1HOUR
WQ Output Interval=15MIN
WQ Output Selected Increments= 0
WQ Output face flow=0
WQ Output face velocity=0
WQ Output face area=0
WQ Output face dispersion=0
WQ Output cell volume=0
WQ Output cell surface area=0
WQ Output cell continuity=0
WQ Output cumulative cell continuity=0
WQ Output face conc=0
WQ Output face dconc_dx=0
WQ Output face courant=0
WQ Output face peclet=0
WQ Output face adv mass=0
WQ Output face disp mass=0
WQ Output cell mass=0
WQ Output cell source sink temp=0
WQ Output nsm pathways=0
WQ Output nsm derived pathways=0
WQ Create Restart=0
WQ Fixed Restart=0
WQ System Summary=0
WQ Write To DSS=0
Sorting and Armoring Iterations= 10
XS Update Threshold= 0.02
Bed Roughness Predictor= 0
Hydraulics Update Threshold= 0.02
Energy Slope Method= 1
Volume Change Method= 1
Sediment Retention Method= 0
Sediment TS Multiplier= 1
Warm Up Method= 0
XS Weighting Method= 0
Number of US Weighted Cross Sections= 1
Number of DS Weighted Cross Sections= 1
Upstream XS Weight=0
Main XS Weight=1
Downstream XS Weight=0
Number of DS XS's Weighted with US Boundary= 1
Upstream Boundary Weight= 1
Weight of XSs Associated with US Boundary= 0
Number of US XS's Weighted with DS Boundary= 1
Downstream Boundary Weight= 0.5
Weight of XSs Associated with DS Boundary= 0.5
Percentile Method= 0
Sediment Output Level= 3
Mass or Volume Output= 0
Output Increment Type= 1
Profile and TS Output Increment= 1
Transport Output Increment 1
XS Output Flag= 0
XS Output Increment= 10
Read HDF5 Sediment Hotstart= 0
Sediment Hotstart Type= 0
Write Gradation File= 0
Read Gradation Hotstart= 0
Write HDF5 File= 1
Write Binary Output= 1
Write DSS Sediment File= 0
DSS Sediment Output Type= 1
SV Curve= 0
Specific Gage Flag= 0
Subcell Erosion Methods= 0
Subcell Deposition Methods= 0
Advection Scheme= 1
Matrix Solver= 0
Implicit Weighting Factor= 1
Maximum Outer Loop Convergence Iterations= 5
Convergence Maximum Absolute= 0.001
Convergence RMSE= 0.0001
Grain Fractions Max Abs Error= 0.001
Max Subgrid Regions= 1
Max Subgrid Length Scale= 3.402823E+38
Initial Layer Thickness= 3.402823E+38
Min Layer Thickness= 3.402823E+38
Max Layer Thickness= 3.402823E+38
Number of Layers= 5

--- FISHHTCHRN.f01 (steady flow) ---

Flow Title=Flow
Program Version=6.20
Number of Profiles= 1
Profile Names=P100yr
River Rch & RM=FISHHTCHRN,Main,9332
     501
River Rch & RM=FISHHTCHRN,Main,7175
     565
River Rch & RM=FISHHTCHRN,Main,4671
     645
River Rch & RM=FISHHTCHRN,Main,1846
     735
Boundary for River Rch & Prof#=FISHHTCHRN,Main            , 1
Up Type= 0
Dn Type= 3
Dn Slope=0.01912
DSS Import GetInterval= 0
DSS Import GetPeak= 0
DSS Import FillOption= 0

--- FISHHTCHRN.g01 (geometry) ---

Geom Title=Geometry
Program Version=6.20

River Reach=FISHHTCHRN      ,Main
Reach XY= 30
      2290825.86      577548.311     2290877.943      577689.717
     2290824.557      577901.696     2290867.526      578286.331
      2291018.22      578520.186     2290705.699      579005.486
     2290687.001      579509.057     2290253.405      579610.608
     2290060.723      579942.366     2289871.347      580008.792
     2289771.661      580317.366     2289615.717      580334.114
      2289577.22      580463.413     2289622.457      580626.373
     2289350.625      580849.061     2289436.938      581034.554
     2289443.407      581237.269     2289331.092      581283.348
     2289156.303      581219.886     2288845.272      581463.025
     2288702.202      581670.233     2287956.383      582078.998
     2287879.882      582407.997     2287516.637      582620.424
     2287186.793      583094.179     2286927.247      583103.539
     2286927.778      583217.552     2286758.101      583561.174
      2286382.46      583694.111     2286337.045      583782.603

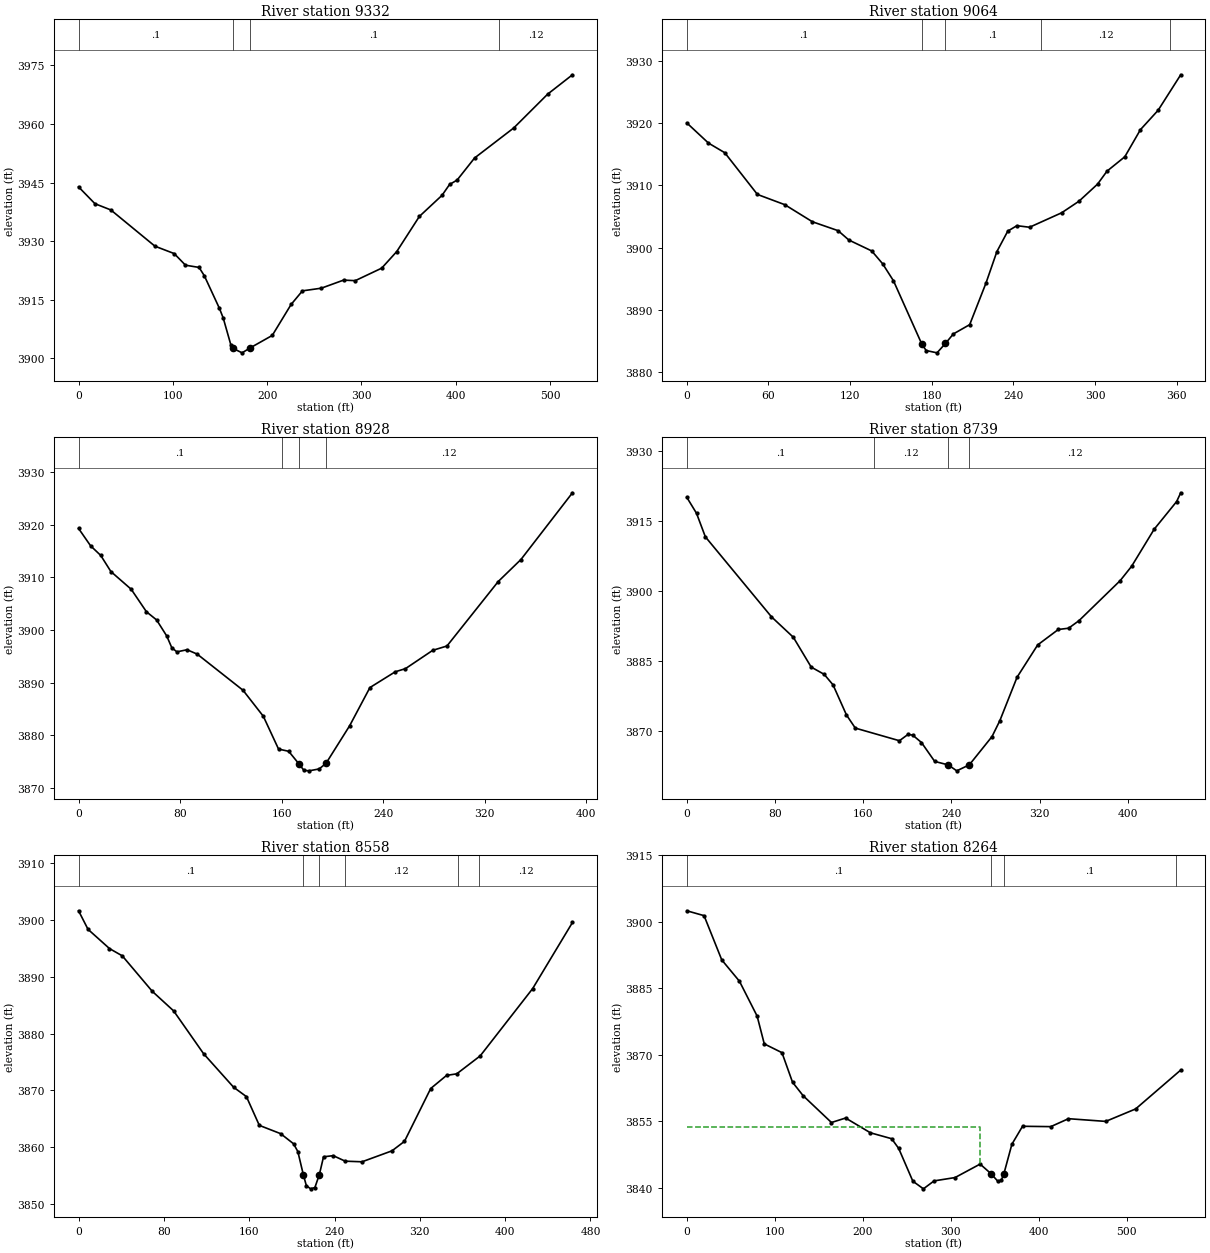
Type RM Length L Ch R = 1 ,9332    ,266.8,268.2,268
XS GIS Cut Line= 3
 2290650.8113817577562.952969191     2290826.548      577558.287
2291174.42585348577553.185424506
#Sta/Elev= 30
       0 3943.89    17.4 3939.58    34.2 3937.99      81  3928.7   101.4 3926.81
   113.4 3923.83   127.8 3923.26   133.4 3921.11   149.4 3912.76   153.4  3910.3
   161.4  3903.5  163.753902.525   173.4 3901.38   181.4 3902.57   205.4 3905.84
   225.4 3913.78   237.4 3917.26   257.4 3917.94     281 3920.01   293.4 3919.87
   321.4 3923.07   337.4 3927.33   361.4 3936.33   385.4 3941.73   393.4 3944.51
   401.4 3945.64   419.9 3951.29   461.5    3959   497.5 3967.67   523.7 3972.61
#Mann= 4 ,-1,0
       0      .1       0  163.75    .045       0   181.4      .1       0
   445.8     .12       0
Bank Sta=163.75,181.4
XS Rating Curve= 0 ,0
Exp/Cntr=0.3,0.1

Type RM Length L Ch R = 1 ,9064    ,136.7,136.1,135.6
XS GIS Cut Line= 3
2290644.28361195577800.1452282272290919.71699366577804.339645208
2291005.00347226  577784.7656993
#Sta/Elev= 30
       0    3920    15.9 3916.77    27.9 3915.22    51.9 3908.53      72 3906.89
    92.3 3904.15   111.2 3902.72   119.1 3901.22   135.9 3899.47   143.9 3897.42
   151.9 3894.68  172.573884.602   175.9  3883.5   183.9 3883.13   190.1 3884.64
   195.9 3886.16   207.9 3887.65   219.9 3894.33   227.9 3899.37   235.9 3902.65
   242.6 3903.52   251.9 3903.27   275.5 3905.59   288.2 3907.44   301.9 3910.19
   308.8 3912.26   321.9 3914.57   333.4 3918.92   346.4 3922.03     363 3927.72
#Mann= 5 ,-1,0
       0      .1       0  172.57    .045       0   190.1      .1       0
     260     .12       0  355.47      .1       0
Bank Sta=172.57,190.1
XS Rating Curve= 0 ,0
Exp/Cntr(USF)=0,0
Exp/Cntr=0.3,0.1

Type RM Length L Ch R = 1 ,8928    ,189.3,188.9,189.3
XS GIS Cut Line= 3
2290638.69105598577945.5516835432290912.72629869577935.764710589
2291023.17927917 577903.60751374
#Sta/Elev= 30
       0  3919.3     9.5    3916    17.5 3914.17    25.5 3911.11    41.5 3907.75
    53.5 3903.48    61.5 3901.93    69.5 3898.88    73.5 3896.64    77.5 3895.87
    85.5 3896.27    93.5 3895.44   129.6 3888.58   145.6 3883.64   157.6 3877.41
   165.6 3876.99   173.6 3874.62   177.6 3873.37   181.6 3873.28   189.6 3873.64
     195  3874.7   213.6 3881.83   229.6 3889.09   249.6 3892.09   257.6 3892.68
   279.1 3896.16   290.3 3896.98   330.7 3909.22   348.6  3913.4   389.2 3926.07
#Mann= 4 ,-1,0
       0      .1       0     160     .12       0   173.6    .045       0
     195     .12       0
Bank Sta=173.6,195
XS Rating Curve= 0 ,0
Exp/Cntr(USF)=0,0
Exp/Cntr=0.3,0.1

Type RM Length L Ch R = 1 ,8739    ,181.6,181.2,180.5
XS GIS Cut Line= 3
2290627.35498848578113.3941518062290907.93791263578113.501504118
2291051.27194961578027.099591438
#Sta/Elev= 30
       0 3920.15     8.8 3916.73    16.8 3911.69    76.8 3894.51    96.6 3890.13
   112.8 3883.73   124.6 3882.17   132.6 3879.92   144.8 3873.45   152.8 3870.64
   192.8 3867.93   200.5 3869.27   204.8 3869.14   212.8 3867.55   224.8 3863.49
   237.1 3862.74   244.8 3861.47   256.2 3862.76   276.8 3868.83   283.9 3872.25
   299.5 3881.56   318.2 3888.49   336.9  3891.8   346.2 3892.07   355.6 3893.68
     393 3902.28   403.4 3905.37   423.8  3913.3   444.2 3919.25   447.9 3921.13
#Mann= 4 ,-1,0
       0      .1       0     170     .12       0   237.1    .045       0
   256.2     .12       0
Bank Sta=237.1,256.2
XS Rating Curve= 0 ,0
Exp/Cntr=0.3,0.1

Type RM Length L Ch R = 1 ,8558    ,291.5,293.9,294.1
XS GIS Cut Line= 3
2290651.27430692578309.8005483732290975.64255339578283.235907498
2291091.68808985578209.134540847
#Sta/Elev= 30
       0 3901.61     8.9 3898.34      29 3894.96      41 3893.68    69.1 3887.44
    89.2 3883.98   117.3 3876.44   145.4 3870.55   157.4  3868.9   169.5 3863.84
   189.5 3862.38   201.6  3860.6   205.6 3859.24   210.83855.127   213.6 3853.23
   217.6 3852.67   221.6  3852.9   225.83855.192   229.7 3858.31   238.8 3858.51
     250 3857.54   265.8 3857.43   293.9 3859.36   305.6 3861.03   330.2 3870.33
   345.1 3872.64   354.6 3872.91   376.6 3876.07   425.8 3887.92   463.1 3899.55
#Mann= 6 ,-1,0
       0      .1       0   210.8    .045       0   225.8      .1       0
     250     .12       0  355.45      .1       0  375.45     .12       0
Bank Sta=210.8,225.8
XS Rating Curve= 0 ,0
Exp/Cntr(USF)=0,0
Exp/Cntr=0.3,0.1

Type RM Length L Ch R = 1 ,8264    ,297.6,299.3,295.1
BEGIN DESCRIPTION:
IFA needed to wet channel
END DESCRIPTION:
XS GIS Cut Line= 3
2290664.61929304578499.0295559742291137.68576035578545.545505644
2291198.42073777578485.023269756
#Sta/Elev= 30
       0 3902.48    19.6 3901.38    39.7 3891.41    59.8  3886.6    79.9 3878.74
      88 3872.48   108.1  3870.5   120.1 3863.84   132.2 3860.79   164.3 3854.76
   180.4 3855.77   208.6 3852.44   232.7 3851.11   240.7 3848.92   256.8 3841.53
   268.8 3839.81   280.9  3841.6   304.7 3842.35   333.2 3845.39   345.5 3843.24
   353.3 3841.53   357.3 3841.76   360.2  3843.2   369.3 3849.86   381.4 3853.91
   413.5 3853.83   433.6 3855.62   475.9 3855.01   509.9 3857.82   561.1 3866.58
#Mann= 4 ,-1,0
       0      .1       0   345.5    .045       0   360.2      .1       0
  555.35     .12       0
#XS Ineff= 2 , 0
          333.14 3853.72
Permanent Ineff=
       F       F
Bank Sta=345.5,360.2
XS Rating Curve= 0 ,0
Exp/Cntr=0.3,0.1

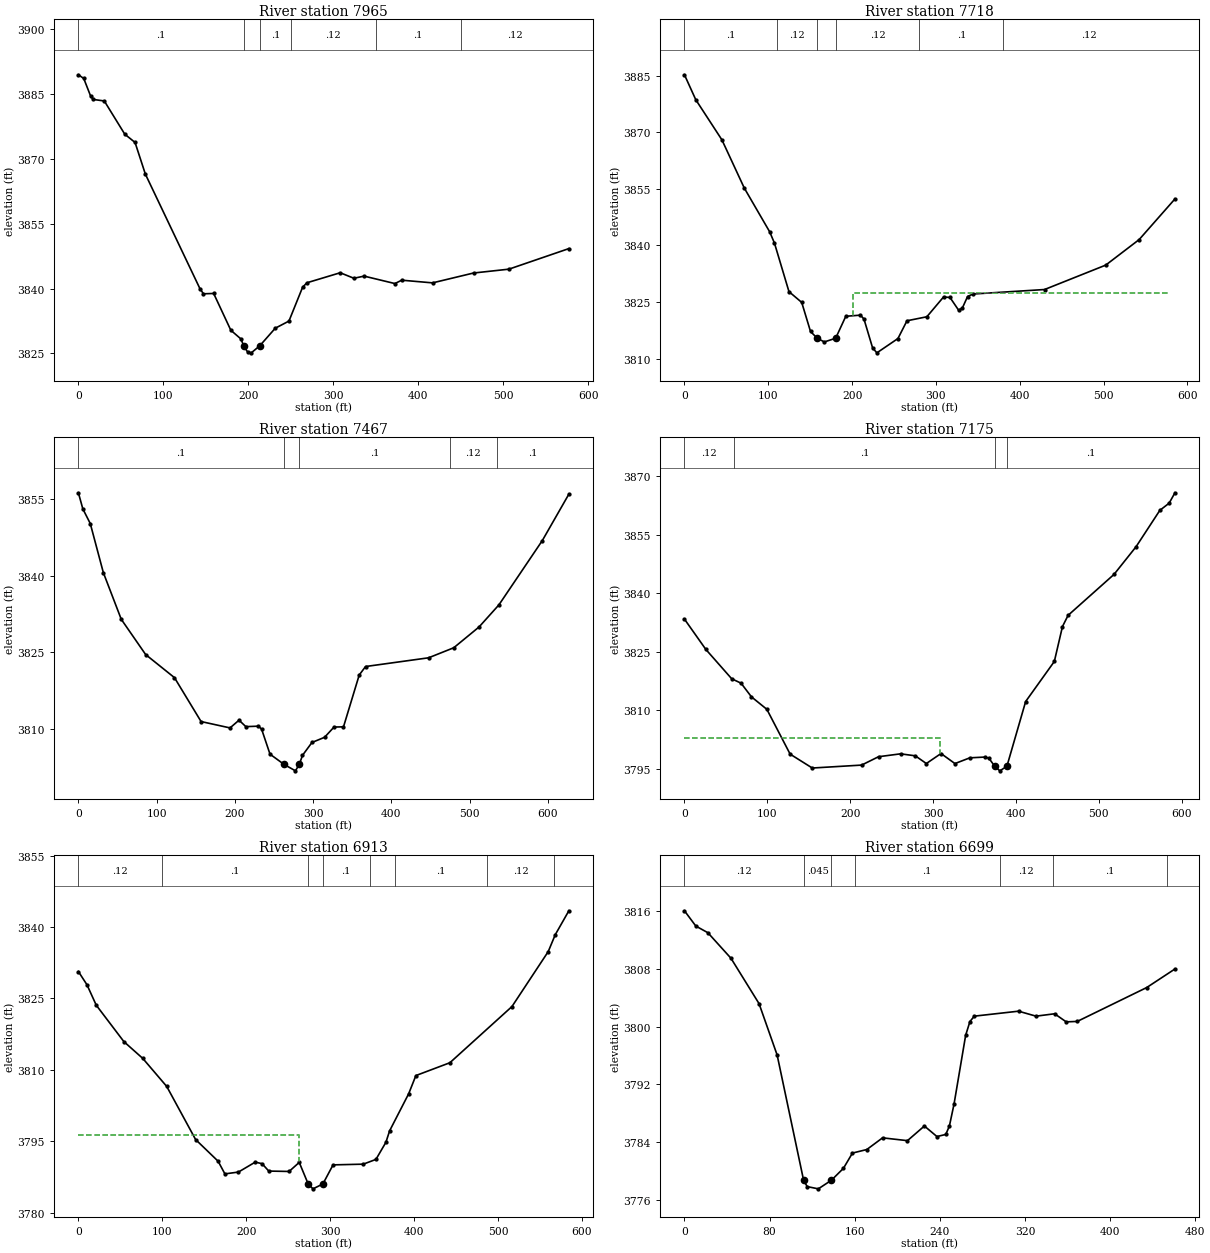
Type RM Length L Ch R = 1 ,7965    ,240.8,246.9,255.9
XS GIS Cut Line= 3
2290649.87616793578748.0834657642291125.24342569 578799.81460852
2291218.91873825578767.657411672
#Sta/Elev= 30
       0 3889.49     6.3 3888.64    14.4 3884.57    17.6 3883.78    30.5 3883.43
    54.6 3875.74    66.7 3873.83    78.8 3866.52   143.1 3839.98   147.2 3838.81
   159.2 3838.89   179.4 3830.38   191.4 3828.34  194.52 3826.76   199.5 3825.24
   203.5 3825.15   213.5 3826.79   231.7 3830.85   247.8  3832.5   263.8  3840.3
   268.9 3841.36   308.1 3843.68   324.2 3842.41   336.3  3842.9   372.5 3841.18
   380.5 3841.96   416.8 3841.34     465 3843.62   506.6 3844.51   577.2 3849.27
#Mann= 6 ,-1,0
       0      .1       0  194.52    .045       0   213.5      .1       0
     250     .12       0     350      .1       0     450     .12       0
Bank Sta=194.52,213.5
XS Rating Curve= 0 ,0
Exp/Cntr(USF)=0,0
Exp/Cntr=0.3,0.1

Type RM Length L Ch R = 1 ,7718    ,256,250.4,239.1
XS GIS Cut Line= 3
2290627.10391135 578850.886670392290757.35437856579003.155946761
2291057.55487676579243.994540217
#Sta/Elev= 30
       0 3885.21    13.5  3878.6    44.7 3867.96    71.4 3855.18   101.7 3843.58
   107.4 3840.58   124.7 3827.73   139.9 3824.88   150.4 3817.17   158.4 3815.38
   166.9  3814.4   180.43815.381   192.5  3821.2     210  3821.5   214.2 3820.45
   224.5  3812.8   229.6 3811.51   254.7  3815.3   265.5 3820.01   289.2 3821.07
   309.1 3826.31   316.8 3826.19   327.1 3822.81   331.5 3823.36   337.8 3826.44
   344.2  3827.1   429.6 3828.29   502.6 3834.76   542.5 3841.53   585.2  3852.3
#Mann= 6 ,-1,0
       0      .1       0     110     .12       0   158.4    .045       0
   180.4     .12       0  280.38      .1       0  380.38     .12       0
#XS Ineff= 1 ,-1
  200.58   578.1 3827.24
Permanent Ineff=
       F
Bank Sta=158.4,180.4
XS Rating Curve= 0 ,0
Exp/Cntr=0.3,0.1

Type RM Length L Ch R = 1 ,7467    ,289.9,292.6,294
XS GIS Cut Line= 4
 2290463.9236818579092.0256581442290586.95991322579201.080499631
2290935.09652259 579241.626530442291039.95694709579280.774422256
#Sta/Elev= 30
       0 3856.14     5.7    3853    15.2 3850.14    31.9 3840.57    54.8 3831.47
      86 3824.59   122.8 3820.09   156.8 3811.53   193.8 3810.29   205.3  3811.8
     214 3810.54   230.1 3810.63   234.1 3810.07   244.9 3805.17     263 3803.16
   277.4 3801.92   282.4  3803.2   286.4 3804.94   298.5 3807.45   314.6 3808.46
   326.7 3810.46   338.8  3810.5   358.9 3820.61     367 3822.26   447.5 3823.96
   479.7 3825.92     512 3829.97   537.4 3834.28   592.9 3846.83   626.8 3855.87
#Mann= 5 ,-1,0
       0      .1       0     263    .045       0   282.4      .1       0
  474.41     .12       0   534.9      .1       0
Bank Sta=263,282.4
XS Rating Curve= 0 ,0
Exp/Cntr(USF)=0,0
Exp/Cntr=0.3,0.1

Type RM Length L Ch R = 1 ,7175    ,253.3,261.7,268.6
XS GIS Cut Line= 3
2290371.74756865579301.1674544072290448.24484014579386.082826579
 2290878.4940388579593.084539673
#Sta/Elev= 30
       0 3833.37    25.8 3825.62      57 3818.11    68.3 3816.98    80.8 3813.49
    99.4  3810.3   127.5 3798.83   154.2 3795.28   213.7 3796.03   234.1 3798.17
   260.7 3798.91   278.5  3798.4   291.8 3796.43   309.5 3798.99   326.3 3796.42
   344.3 3797.89   362.3 3798.08   367.2 3797.81   374.3 3795.73   380.5 3794.56
     389 3795.74   411.6 3812.29   446.2 3822.54     456 3831.46   462.8 3834.34
   518.2 3844.81   544.8 3851.89   573.5  3861.2   584.7 3863.03   591.7 3865.69
#Mann= 4 ,-1,0
       0     .12       0      60      .1       0   374.3    .045       0
     389      .1       0
#XS Ineff= 2 , 0
          308.79 3802.89
Permanent Ineff=
       F       F
Bank Sta=374.3,389
XS Rating Curve= 0 ,0
Exp/Cntr(USF)=0,0
Exp/Cntr=0.3,0.1

Type RM Length L Ch R = 1 ,6913    ,221.4,213.7,202.7
XS GIS Cut Line= 4
 2290338.6174961  579349.8183688 2290435.4118569579450.574781571
2290456.25999428579626.7795963552290694.60322203579747.880082418
#Sta/Elev= 30
       0 3830.66    10.2 3827.89    21.3 3823.59    54.2 3815.95    76.8 3812.41
   105.3 3806.53   139.7 3795.39   166.5 3790.84   174.6 3788.18   190.7 3788.56
   210.8 3790.65   218.9 3790.32   226.9 3788.77   251.1 3788.69   263.2 3790.59
  273.91 3786.04   279.6 3785.04   291.4 3786.07   303.5 3790.07   339.5 3790.22
   354.6 3791.22   366.5 3794.82   370.9 3797.22   393.6    3805   402.2 3808.82
   442.7 3811.51   516.7 3823.31   559.9 3834.84   568.3 3838.39   584.5 3843.41
#Mann= 8 ,-1,0
       0     .12       0     100      .1       0  273.91    .045       0
   291.4      .1       0  347.15     .12       0  377.15      .1       0
  487.15     .12       0  567.15      .1       0
#XS Ineff= 2 , 0
          263.18 3796.32
Permanent Ineff=
       F       F
Bank Sta=273.91,291.4
XS Rating Curve= 0 ,0
Exp/Cntr=0.3,0.1

Type RM Length L Ch R = 1 ,6699    ,314.6,313.8,311.7
XS GIS Cut Line= 4
2290154.83169497579535.3869992952290349.64377611579717.010675447
2290427.57206797579791.0951548532290514.74849436579790.456371119
#Sta/Elev= 30
       0 3816.08    10.7 3813.96      22 3813.04    43.7  3809.5    70.1 3803.21
    87.1 3796.09  112.023778.691   115.4 3777.84   125.8 3777.53   138.1 3778.72
   149.4 3780.37   157.9 3782.49   171.4 3782.98   186.2  3784.6   209.6 3784.21
   225.5 3786.24   237.3 3784.78   245.6 3785.07     249 3786.23   253.4  3789.3
   264.3 3798.82   268.3 3800.72   272.4 3801.47     314 3802.16   330.4 3801.47
   347.9  3801.8   358.8 3800.68   369.2 3800.74   434.5 3805.44     461 3808.01
#Mann= 7 ,-1,0
       0     .12       0  112.02    .045       0   138.1     .12       0
     160      .1       0  296.34     .12       0  346.34      .1       0
  453.87     .12       0
Bank Sta=112.02,138.1
XS Rating Curve= 0 ,0
Exp/Cntr=0.3,0.1

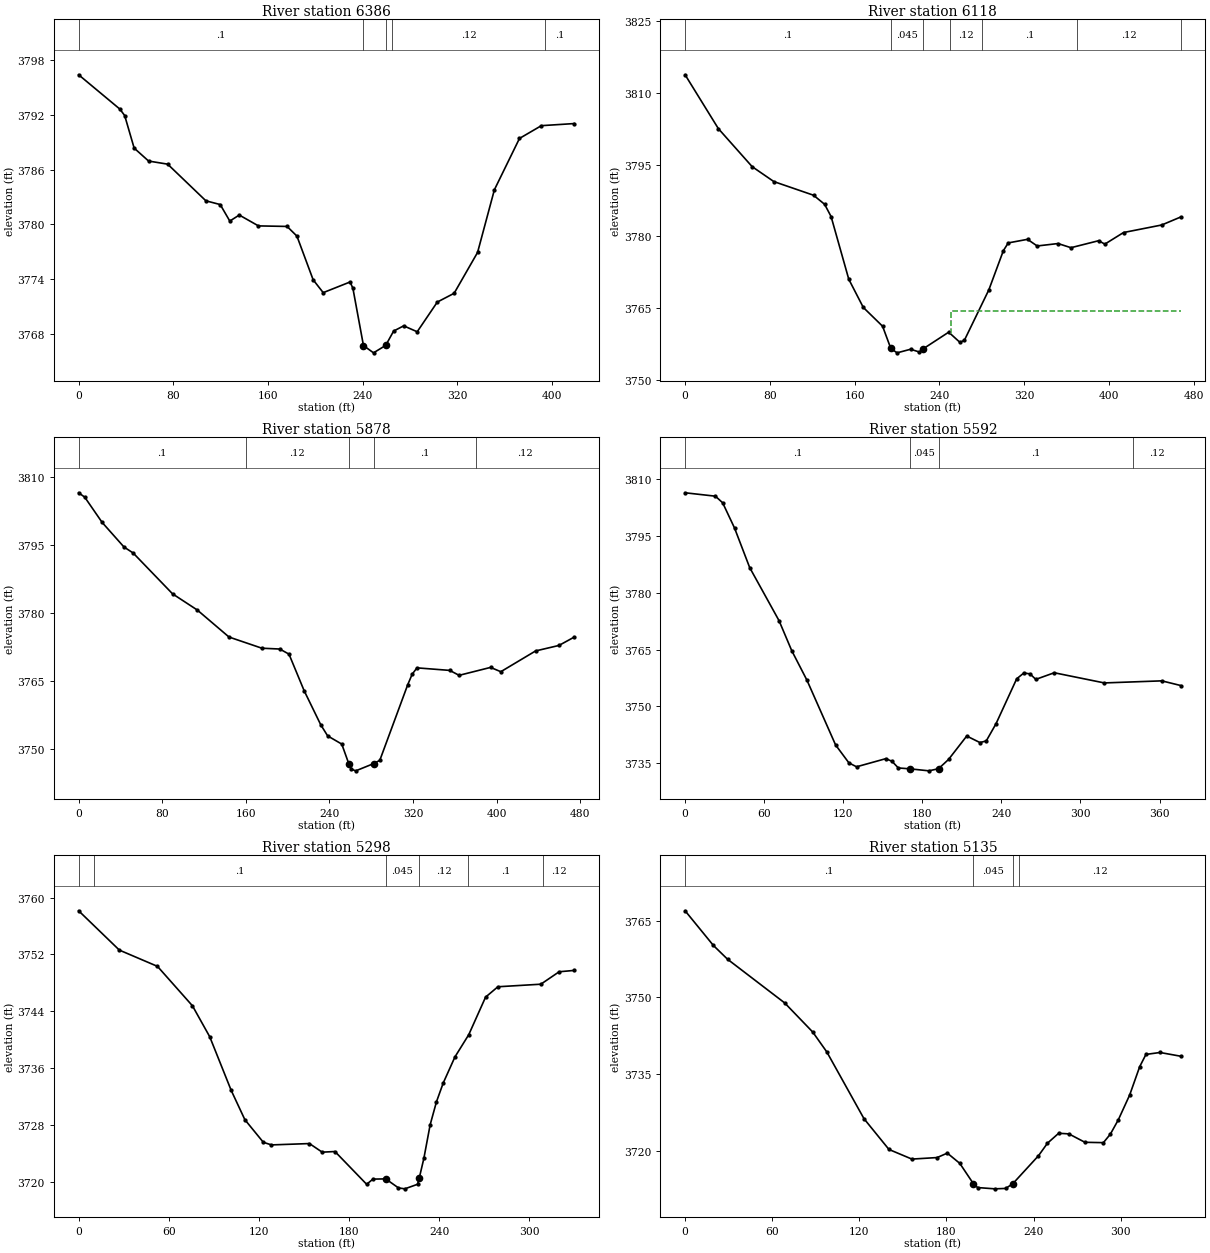
Type RM Length L Ch R = 1 ,6386    ,274.4,268,262.4
XS GIS Cut Line= 3
2290072.83555151 579658.638980482290048.56205409579841.404382408
2290224.90745602579995.567791862
#Sta/Elev= 30
       0 3796.41    34.8 3792.65    38.9 3791.94    46.9 3788.37    59.1 3786.95
    75.2 3786.61   107.5 3782.59   119.6 3782.18   127.7 3780.37   135.7 3781.03
   151.9 3779.84   176.1 3779.78   184.4 3778.72   198.1 3773.93   206.6 3772.52
   229.3 3773.69   231.7 3772.99   240.6 3766.72   249.1 3765.92  259.393766.736
   266.1 3768.31   274.6 3768.88     286 3768.23     303 3771.49   317.2 3772.45
     337 3776.93   351.2  3783.8   372.4 3789.43   390.9 3790.83   418.6 3791.06
#Mann= 5 ,-1,0
       0      .1       0   240.6    .045       0  259.39      .1       0
  264.37     .12       0  394.37      .1       0
Bank Sta=240.6,259.39
XS Rating Curve= 0 ,0
Exp/Cntr=0.3,0.1

Type RM Length L Ch R = 1 ,6118    ,240.7,239.7,238.1
XS GIS Cut Line= 3
2289692.62760955579899.0208130722290051.75052786580095.495605679
2290109.98168293580091.579037818
#Sta/Elev= 30
       0 3813.78    31.4 3802.52    63.3 3794.57    83.8 3791.45   121.2  3788.6
   131.7  3786.7   137.8 3784.14   154.5 3771.03   168.2 3765.14   186.4 3761.21
  194.173756.559   200.1 3755.65   212.8  3756.4   221.2 3755.82     225 3756.53
   248.8 3759.97   259.4 3757.84   263.6 3758.27   286.7 3768.82   300.4 3777.01
     305 3778.63   323.2 3779.38   332.3 3777.99     352  3778.5   364.2 3777.63
   390.3 3779.09   396.2 3778.38   413.8  3780.8   449.9 3782.38   467.7 3784.04
#Mann= 7 ,-1,0
       0      .1       0  194.17    .045       0     225      .1       0
     250     .12       0     280      .1       0     370     .12       0
  467.72      .1       0
#XS Ineff= 2 , 0
                           250.9         3764.48
Permanent Ineff=
       F       F
Bank Sta=194.17,225
XS Rating Curve= 0 ,0
Exp/Cntr(USF)=0,0
Exp/Cntr=0.3,0.1

Type RM Length L Ch R = 1 ,5878    ,278.8,285.6,281.8
XS GIS Cut Line= 3
2289576.12693219580105.3643357932289953.04549893580298.548822032
2290002.39373836580286.899768022
#Sta/Elev= 30
       0 3806.53     5.8 3805.57    22.5 3799.98    43.4 3794.55    52.2 3793.22
    89.9  3784.2   113.6 3780.62   143.9 3774.66   175.4 3772.19   192.5 3772.01
   201.3 3770.88   215.8  3762.8   231.7 3755.27   238.3 3752.82   251.8 3751.01
   258.7 3746.56   260.8 3745.48   265.2  3745.1   282.2 3746.69   288.2 3747.42
   314.9 3764.11   319.2 3766.46   323.8 3767.85   355.1 3767.29   364.1  3766.2
   394.2 3767.95     404    3767   437.3 3771.59   459.6  3772.8   474.2 3774.64
#Mann= 5 ,-1,0
       0      .1       0     160     .12       0   258.7    .045       0
   282.2      .1       0     380     .12       0
Bank Sta=258.7,282.2
XS Rating Curve= 0 ,0
Exp/Cntr=0.3,0.1

Type RM Length L Ch R = 1 ,5592    ,293.7,294.1,288.3
XS GIS Cut Line= 2
 2289460.2365866580245.3115408462289776.20201772580449.160206087
#Sta/Elev= 30
       0 3806.45      23 3805.55    28.5  3803.8    37.5 3797.14      49 3786.68
    71.3 3772.63    80.9 3764.72    92.5 3756.87   114.2 3739.78   124.3 3735.04
   130.1 3734.01   152.3 3736.16     157 3735.46   161.8  3733.7   170.6 3733.47
     185 3732.94  192.333733.513   199.9 3735.95   213.7 3742.14   223.7 3740.42
   228.5 3740.84   235.9 3745.38   251.6 3757.27     257  3758.8   261.7 3758.58
   266.1 3757.12   280.1 3758.87   318.1 3756.18   361.7 3756.73     376  3755.5
#Mann= 4 ,-1,0
       0      .1       0   170.6    .045       0  192.33      .1       0
     340     .12       0
Bank Sta=170.6,192.33
XS Rating Curve= 0 ,0
Exp/Cntr(USF)=0,0
Exp/Cntr=0.3,0.1

Type RM Length L Ch R = 1 ,5298    ,158.5,163.2,162.8
XS GIS Cut Line= 4
2289432.89586247580520.5088270122289533.28569486580580.322985473
2289649.14550041580620.1346220032289737.95609938580638.116412296
#Sta/Elev= 30
       0 3758.15    27.1 3752.62    52.5 3750.33    75.8 3744.78    87.3 3740.43
   101.6 3732.88   110.7 3728.76     123 3725.58   128.4 3725.21   153.7  3725.4
   162.2 3724.19   170.7 3724.28   191.8 3719.67     196  3720.4   204.5 3720.43
     213 3719.16   217.2 3719.03   225.7 3719.67   226.8 3720.52   229.9 3723.31
   234.1 3728.05   238.3 3731.28   242.8 3733.92   250.6 3737.59   259.8 3740.72
     271    3746   279.2 3747.46   307.8 3747.82     320 3749.57     330 3749.76
#Mann= 6 ,-1,0
       0     .12       0      10      .1       0   204.5    .045       0
   226.8     .12       0  259.37      .1       0  309.37     .12       0
Bank Sta=204.5,226.8
XS Rating Curve= 0 ,0
Exp/Cntr=0.3,0.1

Type RM Length L Ch R = 1 ,5135    ,205.6,201.8,203
XS GIS Cut Line= 2
2289336.18851484580593.6048494312289615.81631352580789.344308509
#Sta/Elev= 30
       0 3766.99    19.5 3760.19    29.3 3757.48    68.6 3748.93    87.9 3743.23
    97.6 3739.33   123.2 3726.25   140.4 3720.22   156.2 3718.33   173.6 3718.63
   180.6  3719.5   189.2 3717.49  198.573713.501   201.5 3712.75   213.3  3712.5
   220.8 3712.58  225.673713.493   243.4 3718.99   249.6 3721.45   257.3 3723.39
   264.3 3723.27   275.4 3721.62   288.1 3721.55   292.9 3723.22   298.4 3726.04
   306.2 3730.89   313.1 3736.44   317.4 3738.84   327.1 3739.22   341.3 3738.49
#Mann= 4 ,-1,0
       0      .1       0  198.57    .045       0  225.67      .1       0
     230     .12       0
Bank Sta=198.57,225.67
XS Rating Curve= 0 ,0
Exp/Cntr(USF)=0,0
Exp/Cntr=0.3,0.1

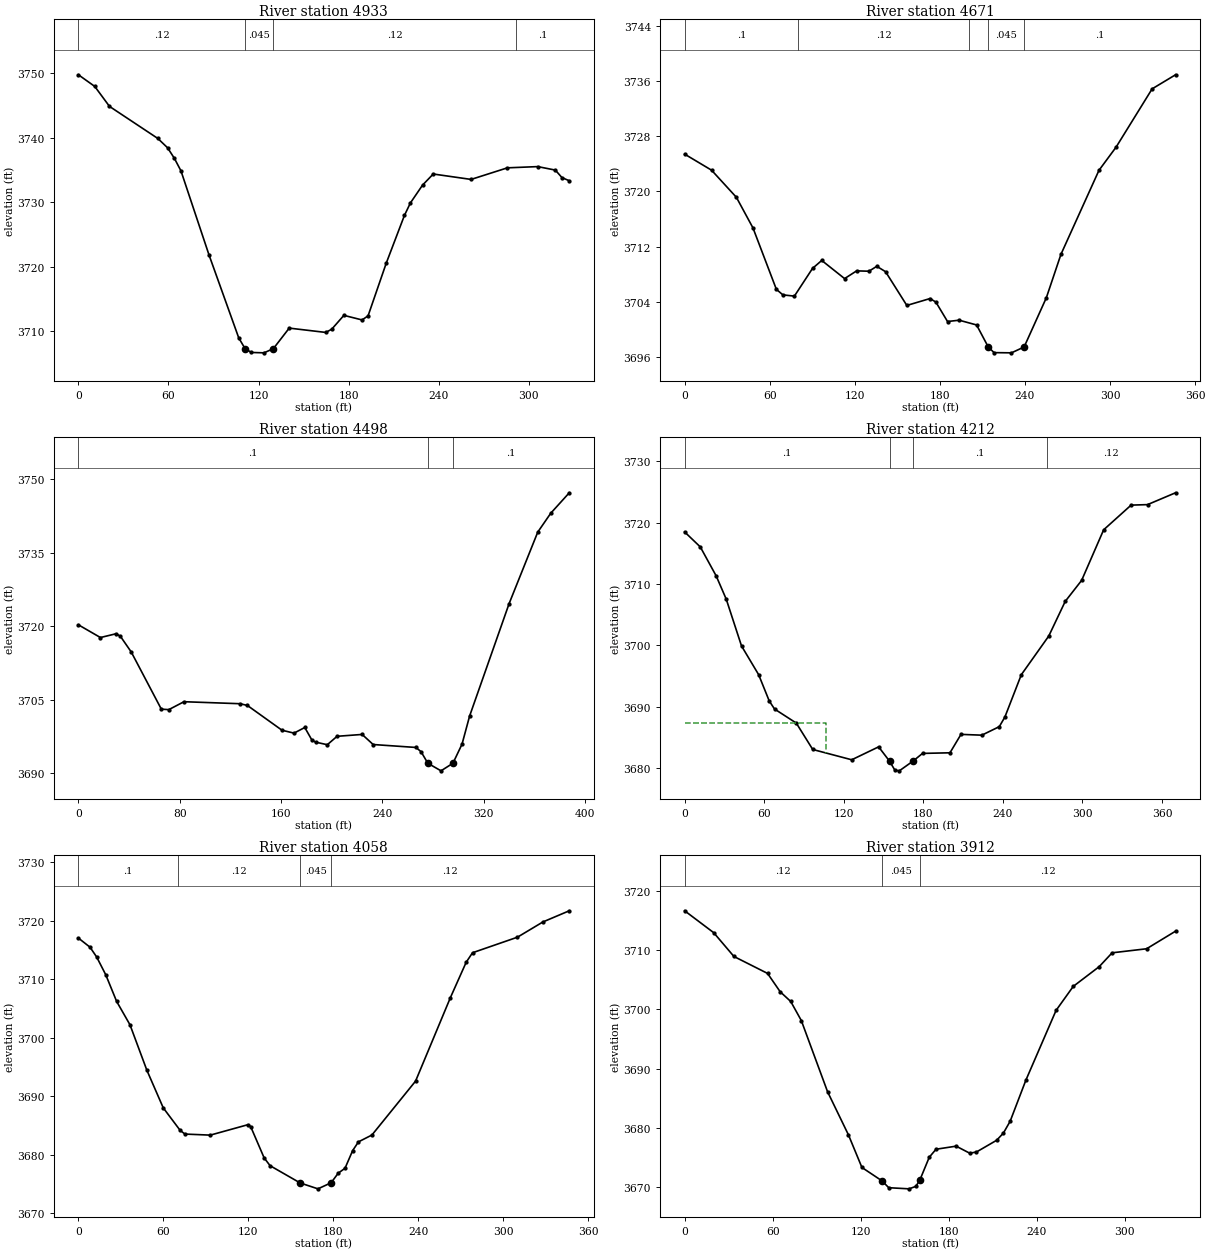
Type RM Length L Ch R = 1 ,4933    ,266.3,262,258.3
XS GIS Cut Line= 4
2289242.58140012580792.2212470712289316.74119644580827.725347577
2289373.38192842580845.8000031082289557.05672471580869.998555915
#Sta/Elev= 30
       0  3749.8    10.9 3747.99    20.7 3744.89    52.9 3739.91    59.4 3738.46
    63.9 3736.83    68.3 3734.88      87 3721.81   106.8 3708.93     111 3707.27
   115.2 3706.68   123.6 3706.62  129.83 3707.27   140.4 3710.46   164.7 3709.79
   168.7 3710.29   176.8 3712.44   188.9 3711.73   192.9 3712.36     205 3720.54
   217.1 3727.95   221.1  3729.9   229.2 3732.67   236.3 3734.39   261.5 3733.55
   285.7 3735.35   305.9 3735.54   317.6    3735     322 3733.84   326.9 3733.34
#Mann= 4 ,-1,0
       0     .12       0     111    .045       0  129.83     .12       0
  291.68      .1       0
Bank Sta=111,129.83
XS Rating Curve= 0 ,0
Exp/Cntr(USF)=0,0
Exp/Cntr=0.3,0.1

Type RM Length L Ch R = 1 ,4671    ,158.9,173.4,181.4
XS GIS Cut Line= 3
2289267.14528332580982.692430725 2289370.3436701581092.495514257
2289561.05428887581049.564985357
#Sta/Elev= 30
       0  3725.4      19 3723.07    36.5 3719.14    48.2  3714.7    64.7  3705.8
    69.3    3705    77.4 3704.82    90.2 3708.84    96.7 3709.99   112.8 3707.36
   121.3 3708.48     130 3708.43   135.5 3709.14   141.7 3708.36   156.7 3703.47
   173.1 3704.47   177.2 3703.95   185.4 3701.14   193.6 3701.33   205.9 3700.64
   214.1 3697.46   218.2 3696.63   230.5  3696.6  239.423697.448   255.1 3704.59
   265.4 3710.88   292.2 3723.05   304.3 3726.42   329.7 3734.86   346.2  3736.9
#Mann= 5 ,-1,0
       0      .1       0      80     .12       0  200.69      .1       0
   214.1    .045       0  239.42      .1       0
Bank Sta=214.1,239.42
XS Rating Curve= 0 ,0
Exp/Cntr(USF)=0,0
Exp/Cntr=0.3,0.1

Type RM Length L Ch R = 1 ,4498    ,276.3,285.6,287.1
XS GIS Cut Line= 2
2289244.20746366581028.6337089342289504.51516255581315.976648305
#Sta/Elev= 30
       0 3720.27    17.4 3717.67    29.7 3718.44    33.1 3717.95    41.7 3714.73
    65.5 3703.03    71.4 3702.93    83.4 3704.55   127.8 3704.14   133.5 3703.78
   160.8 3698.72   170.3 3698.13   178.8 3699.28   184.4 3696.72   187.3 3696.29
   196.6 3695.76   204.3 3697.48   224.1 3697.86   232.8  3695.8   266.6  3695.2
   270.6 3694.34     276 3691.97   286.4 3690.42  295.823691.975     303 3695.88
     309 3701.64   340.2 3724.62   362.8 3739.22   373.1 3743.09   387.7 3747.26
#Mann= 3 ,-1,0
       0      .1       0     276    .045       0  295.82      .1       0
Bank Sta=276,295.82
XS Rating Curve= 0 ,0
Exp/Cntr(USF)=0,0
Exp/Cntr=0.3,0.1

Type RM Length L Ch R = 1 ,4212    ,155,154.1,150.6
XS GIS Cut Line= 3
2289159.39686131 581053.423445542289162.15358423581126.303907637
2289238.52644068581413.585990453
#Sta/Elev= 30
       0 3718.47    11.8 3716.03    23.8  3711.3    31.4  3707.5    42.9 3699.89
    55.8 3695.22    63.8 3690.93    67.8 3689.62    84.2 3687.33    96.6 3683.03
     126 3681.35   146.3 3683.46   154.5 3681.13   158.6 3679.64   161.9 3679.55
  172.323681.153   179.4 3682.39   200.1 3682.49   208.4 3685.49   224.1 3685.36
   237.3 3686.75   241.5 3688.31   253.9 3695.21   274.6 3701.51     287 3707.15
   299.4 3710.58     316 3718.82   336.7 3722.84   349.1 3722.92   370.2 3724.85
#Mann= 4 ,-1,0
       0      .1       0   154.5    .045       0  172.32      .1       0
  272.93     .12       0
#XS Ineff= 2 , 0
          106.94 3687.28
Permanent Ineff=
       F       F
Bank Sta=154.5,172.32
XS Rating Curve= 0 ,0
Exp/Cntr=0.3,0.1

Type RM Length L Ch R = 1 ,4058    ,145.3,146,146.8
XS GIS Cut Line= 4
 2288965.2214919581193.6148525142289026.37609148581231.326855583
2289134.41588405581399.5020044062289200.66670026581434.156277497
#Sta/Elev= 30
       0 3717.07     8.2 3715.51    12.9 3713.83    19.3  3710.8      27 3706.23
    36.4 3702.24    48.3 3694.48    59.9 3688.02    71.8 3684.18    75.2 3683.54
    93.1 3683.36   119.6 3685.14   121.6 3684.82   131.1 3679.47   135.3 3678.13
   156.6 3675.17   169.1 3674.17   178.4 3675.21   183.4 3676.85   188.2 3677.69
   193.6 3680.72   197.7 3682.21   207.2 3683.38     238  3692.6   262.6 3706.89
   273.7 3712.92   278.2 3714.56   309.9 3717.22   327.9 3719.83   346.5 3721.74
#Mann= 4 ,-1,0
       0      .1       0      70     .12       0   156.6    .045       0
   178.4     .12       0
Bank Sta=156.6,178.4
XS Rating Curve= 0 ,0
Exp/Cntr(USF)=0,0
Exp/Cntr=0.3,0.1

Type RM Length L Ch R = 1 ,3912    ,160.2,156.5,151.9
XS GIS Cut Line= 2
2288884.70126913581263.9426420222289048.79944465581555.446233315
#Sta/Elev= 30
       0  3716.6    19.8 3712.91    33.6  3708.9    56.5 3706.05    65.1 3702.96
    72.3 3701.32    79.5 3698.11    97.4 3686.11   111.6 3678.86   120.8 3673.36
   134.5  3671.1   139.1 3669.95   152.9 3669.76   157.5 3670.17  160.173671.177
   166.7 3675.09   171.3 3676.43     185 3676.95   194.2 3675.77   198.8 3675.96
   212.6 3677.94   217.2 3679.15   221.8 3681.14   232.5 3688.05   253.1 3699.82
   264.8 3703.86   282.5 3707.19   291.3 3709.52   314.8  3710.2   334.5 3713.16
#Mann= 3 ,-1,0
       0     .12       0   134.5    .045       0  160.17     .12       0
Bank Sta=134.5,160.17
XS Rating Curve= 0 ,0
Exp/Cntr(USF)=0,0
Exp/Cntr=0.3,0.1

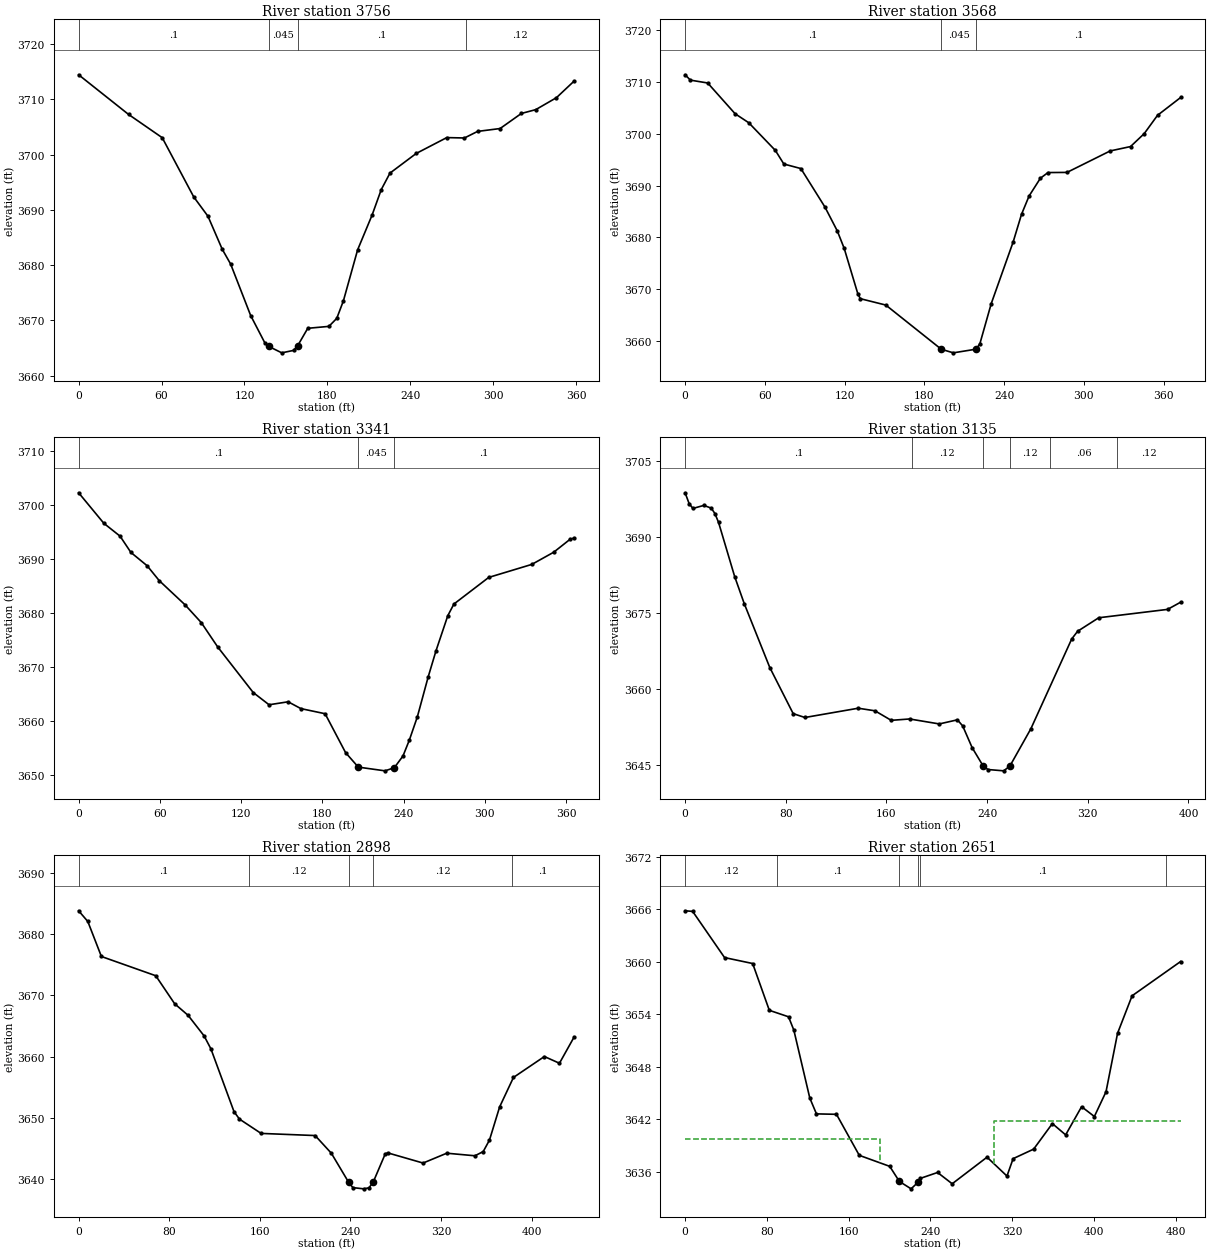
Type RM Length L Ch R = 1 ,3756    ,184.3,188.1,190.8
XS GIS Cut Line= 2
2288715.55783915581387.026466093 2288993.8112672 581613.29848451
#Sta/Elev= 30
       0 3714.44    36.1 3707.27    60.5 3703.05    83.3 3692.33    93.6 3688.83
   103.9 3682.87     110 3680.18   124.5 3670.86   134.8 3665.89  137.463665.288
     147 3664.11   155.5 3664.55   158.4 3665.35   165.8 3668.55   181.1  3668.9
   186.8 3670.35   191.6 3673.52   201.9 3682.76   212.4 3689.07     219 3693.66
   225.3 3696.64   244.3  3700.2   266.4 3703.07   279.2    3703   288.7 3704.19
     305 3704.71   320.4 3707.44   330.8 3708.13   345.8  3710.3   358.6 3713.31
#Mann= 4 ,-1,0
       0      .1       0  137.46    .045       0   158.4      .1       0
     280     .12       0
Bank Sta=137.46,158.4
XS Rating Curve= 0 ,0
Exp/Cntr(USF)=0,0
Exp/Cntr=0.3,0.1

Type RM Length L Ch R = 1 ,3568    ,224.7,227.1,227.7
XS GIS Cut Line= 2
2288605.65855211581479.8648956612288839.10413383581770.569228886
#Sta/Elev= 30
       0  3711.3       4 3710.27      17 3709.72    37.6 3703.81    47.9 3702.07
    67.9 3696.75    74.3 3694.13    87.1 3693.26   105.2 3685.86   114.5 3681.26
   119.7  3677.9   129.9 3669.21   131.8 3668.23     151    3667  192.73  3658.5
   201.8 3657.81     219 3658.52   221.8 3659.59   230.3 3667.27   246.8 3679.14
   253.1 3684.46   258.8 3687.99   267.3  3691.4     273 3692.49   287.3 3692.52
   319.8 3696.65   335.1 3697.49   345.4 3699.98   355.4  3703.5   372.8 3706.93
#Mann= 3 ,-1,0
       0      .1       0  192.73    .045       0     219      .1       0
Bank Sta=192.73,219
XS Rating Curve= 0 ,0
Exp/Cntr(USF)=0,0
Exp/Cntr=0.3,0.1

Type RM Length L Ch R = 1 ,3341    ,205.6,205.9,205.9
XS GIS Cut Line= 4
 2288498.5208957581554.5981536392288495.41195996581682.064518895
 2288572.0990415  581805.38563652288659.14924216581838.547617705
#Sta/Elev= 30
       0 3702.28    18.6 3696.63    30.6 3694.24    38.6 3691.23    50.6 3688.76
    59.5 3686.01    78.6 3681.52    90.6 3678.22   102.6 3673.75   128.9 3665.28
   140.6 3663.01   154.7 3663.56   164.1  3662.3     182 3661.35   197.1 3654.15
   206.5 3651.46   226.2 3650.77  233.083651.345   239.5 3653.52   244.2 3656.47
   250.1 3660.77   258.1 3668.17   263.9 3673.03   272.6 3679.52   277.1 3681.67
   302.8  3686.6   334.6 3689.01   350.8 3691.27   362.7 3693.63   365.9 3693.91
#Mann= 3 ,-1,0
       0      .1       0   206.5    .045       0  233.08      .1       0
Bank Sta=206.5,233.08
XS Rating Curve= 0 ,0
Exp/Cntr(USF)=0,0
Exp/Cntr=0.3,0.1

Type RM Length L Ch R = 1 ,3135    ,236.7,236.2,235.7
XS GIS Cut Line= 3
2288245.66078901581659.265656817  2288400.071264581920.416258804
2288486.08515275581948.396680445
#Sta/Elev= 30
       0 3698.75     3.2 3696.62     6.2 3695.66    14.9 3696.26    20.8 3695.72
    23.7 3694.65    26.6  3692.9    39.4 3682.22      47 3676.89    67.3 3664.29
    85.9 3655.19    95.2 3654.43   137.6 3656.26   150.9 3655.75   163.8 3653.87
   178.4 3654.14     202 3653.16   216.4 3653.97   220.6 3652.77   228.1 3648.49
   236.9 3644.85   240.7 3644.17   253.2 3643.91  258.143644.866   274.8 3652.22
   307.2  3669.9   311.9 3671.43   328.7  3674.1   383.4 3675.75   393.8 3677.17
#Mann= 6 ,-1,0
       0      .1       0     180     .12       0   236.9    .045       0
  258.14     .12       0     290     .06       0  343.38     .12       0
Bank Sta=236.9,258.14
XS Rating Curve= 0 ,0
Exp/Cntr(USF)=0,0
Exp/Cntr=0.3,0.1

Type RM Length L Ch R = 1 ,2898    ,248.8,247.6,243.6
XS GIS Cut Line= 4
2288072.04434547581765.0790600592288073.63301151581845.801801093
2288227.00717459582082.0809171772288301.01139896582094.697382298
#Sta/Elev= 30
       0 3683.86     8.1 3682.11    20.1 3676.38    68.1 3673.23    84.8 3668.64
    96.6 3666.76   110.8 3663.38   116.8 3661.26   137.2 3650.98     142 3649.77
   161.1 3647.43   208.8 3647.08   223.1 3644.19   238.3 3639.46   242.1 3638.56
   251.7 3638.36   256.4 3638.53   260.3 3639.56   270.7 3644.08     273 3644.24
   304.1 3642.58     325 3644.19   349.9 3643.77   357.2 3644.46   362.7 3646.33
   371.7 3651.77   383.9 3656.59   411.2 3660.01   424.5 3658.91   437.5 3663.22
#Mann= 5 ,-1,0
       0      .1       0  150.74     .12       0   238.3    .045       0
   260.3     .12       0  382.43      .1       0
Bank Sta=238.3,260.3
XS Rating Curve= 0 ,0
Exp/Cntr(USF)=0,0
Exp/Cntr=0.3,0.1

Type RM Length L Ch R = 1 ,2651    ,259,256.4,251.1
XS GIS Cut Line= 2
2287778.52946558 581954.790652382288150.56544222582265.684226175
#Sta/Elev= 30
       0 3665.83     7.4 3665.76    38.6 3660.48    66.1  3659.8    82.4 3654.45
   101.2 3653.71   106.4 3652.18     122 3644.42   128.5 3642.61   148.1 3642.56
   170.4 3637.87   200.2 3636.61   209.6 3634.89   221.1 3634.04   228.3 3634.84
     230 3635.23     247 3635.91   261.3 3634.62   295.4 3637.66   314.9  3635.5
   320.9 3637.49     341 3638.58   359.3  3641.5   372.3 3640.21   387.9 3643.43
   400.4 3642.31   411.8 3645.14   423.1 3651.83   437.3 3656.11   484.8 3660.03
#Mann= 6 ,-1,0
       0     .12       0      90      .1       0   209.6    .045       0
   228.3     .12       0     230      .1       0     470     .06       0
#XS Ineff= 2 , 0
          190.61 3639.72  302.17         3641.79
Permanent Ineff=
       F       F
Bank Sta=209.6,228.3
XS Rating Curve= 0 ,0
Exp/Cntr(USF)=0,0
Exp/Cntr=0.3,0.1