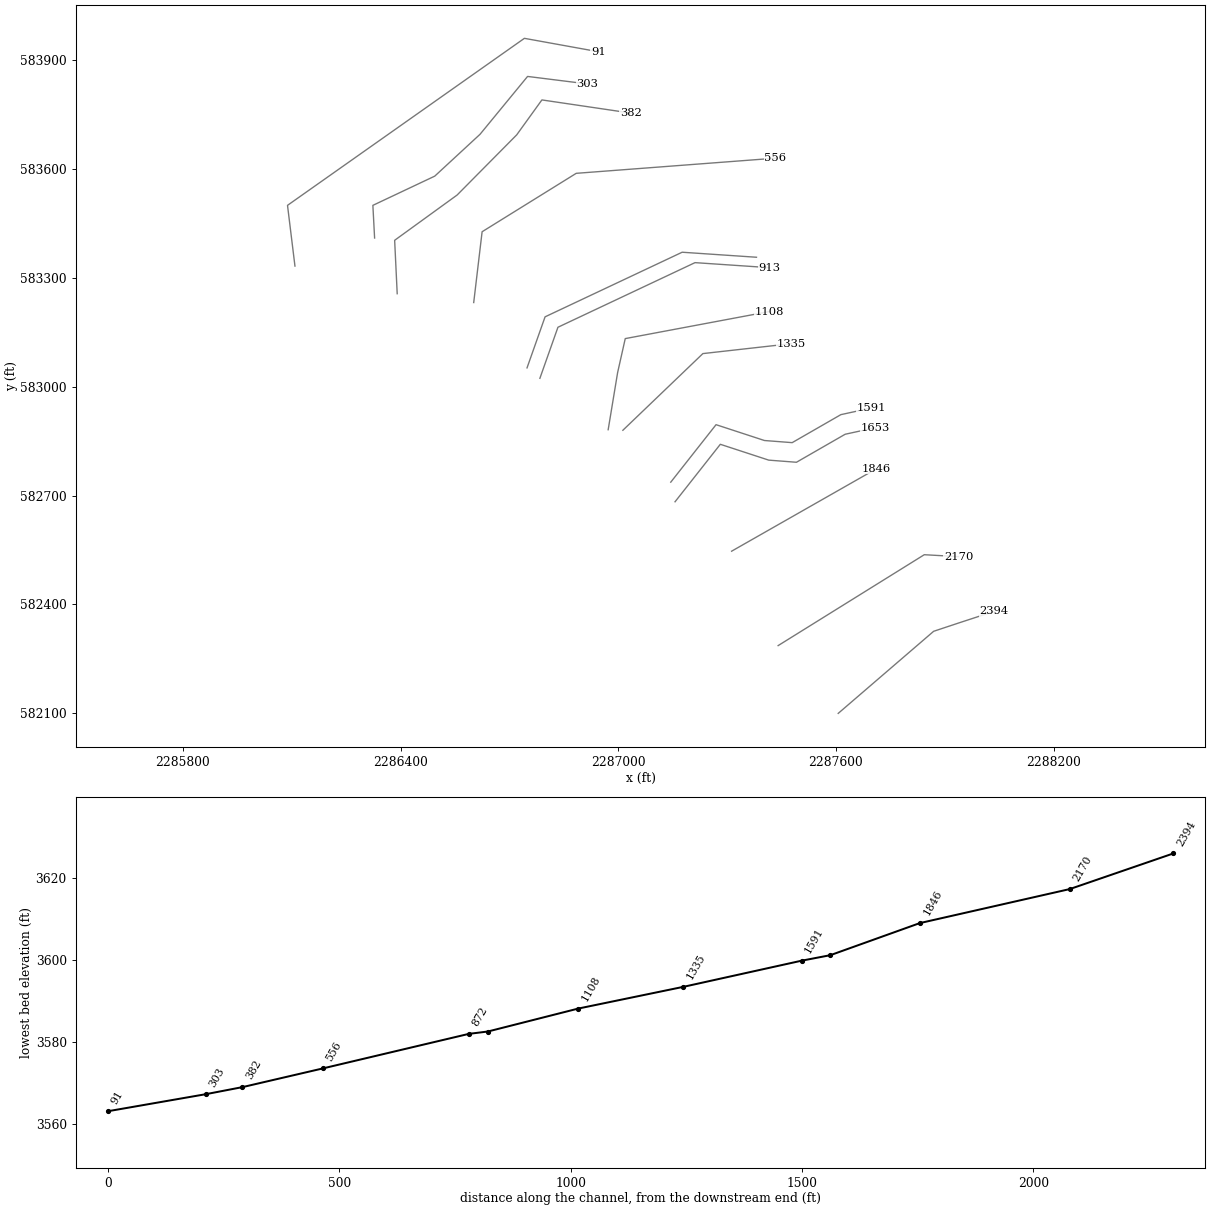
HEC-RAS study FISHHTCHRN.prj: FISHHTCHRN

--- FISHHTCHRN.g01 (geometry) --- (continued)

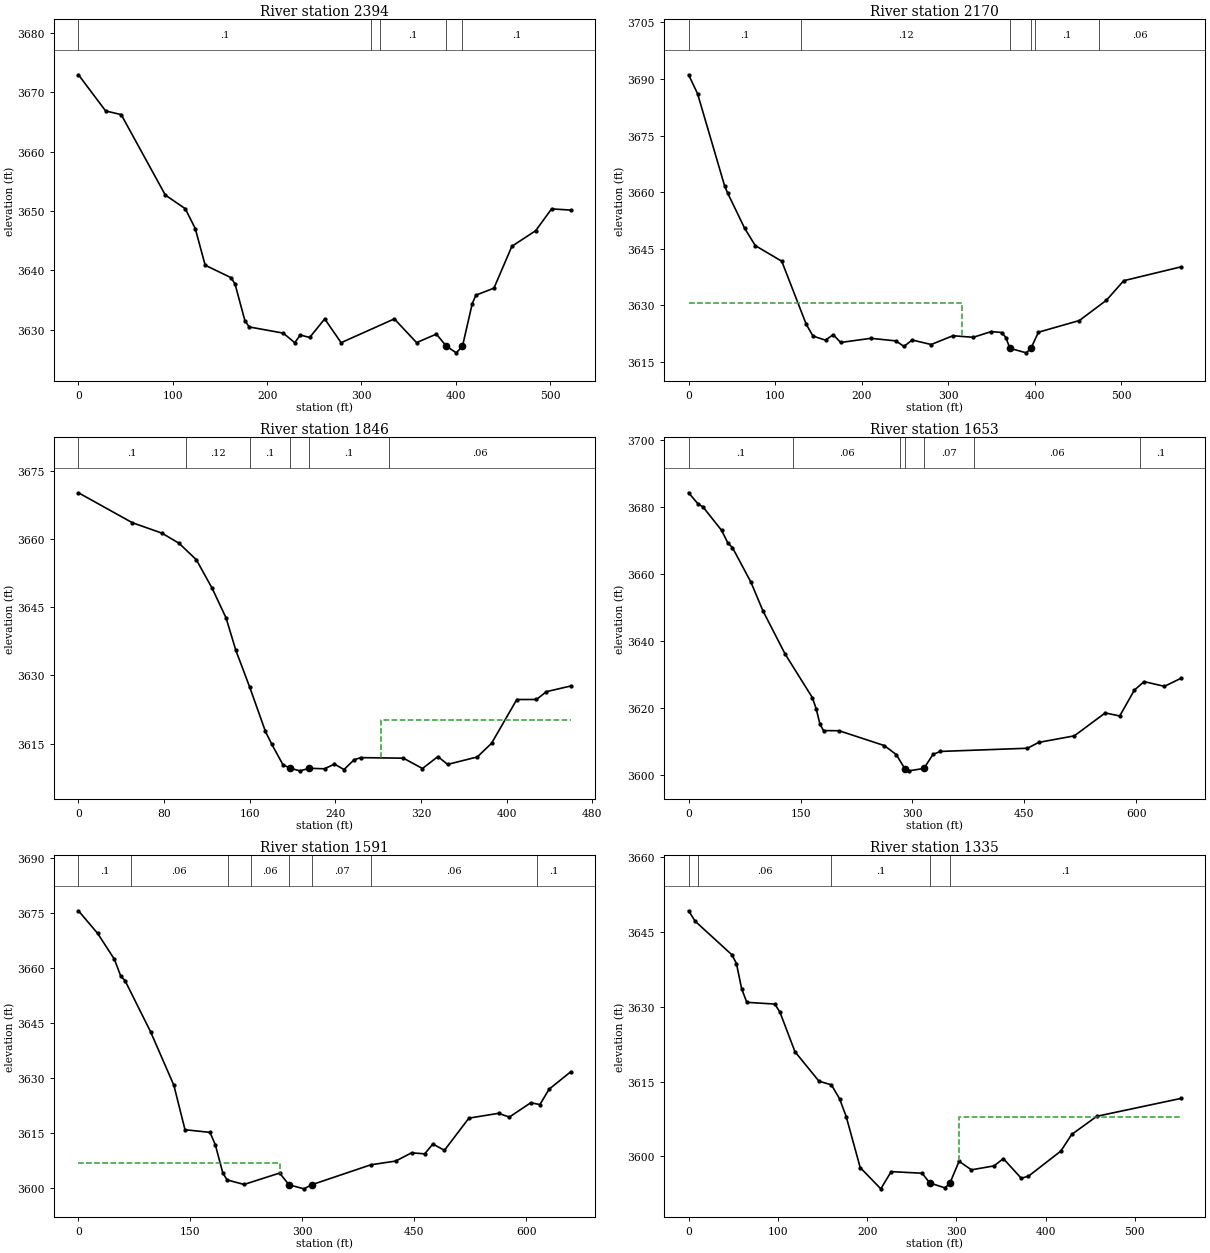
Type RM Length L Ch R = 1 ,2394    ,222.9,224.1,223.8
XS GIS Cut Line= 4
 2287606.3285663582099.625992309 2287869.4263328582325.922633026
2287939.94877478582349.3252267192288035.28947075582380.538748019
#Sta/Elev= 30
       0 3672.93    28.8 3666.84    45.3 3666.22    92.1 3652.66   113.2 3650.37
   123.8 3647.02   134.3 3640.85   161.9 3638.73     166 3637.64   176.5 3631.45
   181.1 3630.44   217.1  3629.4   229.3 3627.78     235 3629.09   245.1 3628.67
     261  3631.8   278.4 3627.79   334.8  3631.8   358.4  3627.8   379.4 3629.24
   389.8 3627.22   400.5 3626.08  407.053627.198   417.4 3634.38   421.3  3635.8
   440.4 3636.98   459.4 3644.03   484.7 3646.67   501.5 3650.34   521.7 3650.13
#Mann= 5 ,-1,0
       0      .1       0     310     .12       0     320      .1       0
   389.8    .045       0  407.05      .1       0
Bank Sta=389.8,407.05
XS Rating Curve= 0 ,0
Exp/Cntr(USF)=0,0
Exp/Cntr=0.3,0.1

Type RM Length L Ch R = 1 ,2170    ,326.6,324.1,329.3
XS GIS Cut Line= 3
2287440.68932014582286.4727825272287843.57176691582537.021846829
2287938.09011766582531.719330595
#Sta/Elev= 30
       0 3691.11    10.3 3686.12    41.8  3661.5    45.2 3659.71    64.7 3650.44
    77.1  3645.8   107.7 3641.66     136 3624.93   143.9  3621.8   158.4 3620.73
   167.1  3622.2   175.8 3620.12   210.7 3621.22   239.6 3620.54     249 3619.07
   258.5 3620.77   280.4 3619.58   305.6  3621.9   329.1 3621.49   350.1 3623.02
   362.1 3622.76   366.8 3621.42   371.5 3618.57   390.4 3617.37   395.83618.564
   404.5 3622.84   451.8 3625.94   483.1 3631.32   503.1  3636.5   569.1 3640.16
#Mann= 6 ,-1,0
       0      .1       0     130     .12       0   371.5    .045       0
   395.8     .12       0     400      .1       0  474.44     .06       0
#XS Ineff= 2 , 0
          316.25 3630.48
Permanent Ineff=
       F       F
Bank Sta=371.5,395.8
XS Rating Curve= 0 ,0
Exp/Cntr(USF)=0,0
Exp/Cntr=0.3,0.1

Type RM Length L Ch R = 1 ,1846    ,205.9,193.3,188.2
XS GIS Cut Line= 2
 2287312.4370763582546.7230625032287711.89338282582774.171493262
#Sta/Elev= 30
       0 3670.12    50.3 3663.55    77.9 3661.26    93.9 3659.04   110.1 3655.41
   124.8 3649.18   137.8 3642.68     147 3635.52     160  3627.4   174.6 3617.73
   180.5 3614.92   190.9 3610.44   197.6 3609.64   206.8 3609.06   215.7 3609.62
   229.8 3609.51   239.1 3610.54     248 3609.34   257.5  3611.5   263.7 3611.96
   303.5 3611.84   321.3 3609.57   335.7 3612.19   344.8 3610.47   372.5 3612.11
   385.8  3615.1   409.4 3624.72   427.8 3624.73     437 3626.44   459.7 3627.69
#Mann= 6 ,-1,0
       0      .1       0     100     .12       0     160      .1       0
   197.6    .045       0   215.7      .1       0     290     .06       0
#XS Ineff= 2 , 0
                          282.32         3620.17
Permanent Ineff=
       F       F
Bank Sta=197.6,215.7
XS Rating Curve= 0 ,0
Exp/Cntr(USF)=0,0
Exp/Cntr=0.3,0.1

Type RM Length L Ch R = 1 ,1653    ,59.1,62.2,56.7
XS GIS Cut Line= 6
2287156.48336456582682.9582187662287281.31701508582841.412627429
2287414.78362631582797.7631696682287491.17017739582791.887281123
2287625.47620127582869.1132448542287708.26376161582887.147261237
#Sta/Elev= 30
       0 3684.16      13 3680.74    18.9 3680.04    44.1 3672.98    52.6 3669.19
    58.8 3667.79    83.5  3657.5    99.6 3648.95   129.5    3636   165.8 3623.09
   170.9  3619.8     176 3615.19   180.8 3613.23   201.7 3613.19   262.2 3608.77
   278.3 3606.08   289.8 3601.88   295.2 3601.23   315.3 3601.94   327.6 3606.14
   337.6 3607.02   454.2 3607.97   469.2 3609.71   516.9 3611.66   558.4  3618.5
   577.8 3617.59   597.5 3625.31   610.5 3627.84   637.8 3626.43   659.7 3628.81
#Mann= 7 ,-1,0
       0      .1       0     140     .06       0  283.59     .07       0
   289.8    .045       0   315.3     .07       0  382.61     .06       0
  604.99      .1       0
Bank Sta=289.8,315.3
XS Rating Curve= 0 ,0
Exp/Cntr(USF)=0,0
Exp/Cntr=0.3,0.1

Type RM Length L Ch R = 1 ,1591    ,244.5,255.3,271.2
XS GIS Cut Line= 6
2287144.69385862582737.0288264552287269.52750913582895.483235118
2287402.99412036582851.8337773572287479.38067144582845.957888813
2287613.68669532582923.1838525432287696.47425567582941.217868926
#Sta/Elev= 30
       0 3675.62    25.7 3669.46    48.2  3662.4    56.7 3657.79    62.4  3656.6
    96.6 3642.69   127.9 3628.07   142.8 3615.98   176.3 3615.26   183.5 3611.84
   193.4 3604.25   199.1 3602.32   221.9 3601.07   269.6 3604.18   282.2 3600.98
   302.2 3599.88   312.6 3600.99   391.9 3606.43   425.3 3607.45   446.4 3609.69
   464.1 3609.41     475 3612.09   490.5 3610.37   523.3 3619.14   563.1 3620.45
   577.5 3619.42   606.2 3623.32   618.5 3622.84   630.8 3627.02   659.7 3631.75
#Mann= 8 ,-1,0
       0      .1       0      70     .06       0     200      .1       0
  231.72     .06       0   282.2    .045       0   312.6     .07       0
  392.61     .06       0  614.99      .1       0
#XS Ineff= 2 , 0
           270.3 3606.88
Permanent Ineff=
       F       F
Bank Sta=282.2,312.6
XS Rating Curve= 0 ,0
Exp/Cntr(USF)=0,0
Exp/Cntr=0.3,0.1

Type RM Length L Ch R = 1 ,1335    ,224.4,227.4,237.1
XS GIS Cut Line= 3
2287012.68028316582880.0988261362287233.23097632583091.471144879
2287477.82167259583118.947396731
#Sta/Elev= 30
       0 3649.24     7.3 3647.15    48.5 3640.42    53.6 3638.67    59.4 3633.62
    65.2 3630.89    96.6 3630.54   102.3 3628.93   119.2 3620.98   146.1 3615.08
     160 3614.35   169.2 3611.55   176.6 3607.99   192.3 3597.76   215.4  3593.5
     227 3596.95   261.7 3596.63  270.24 3594.68   287.4 3593.69   292.9 3594.68
   303.1 3599.02   316.9 3597.31   342.3  3598.1   352.7 3599.56   372.8 3595.62
   380.9 3596.04   417.1 3601.06   429.3  3604.4   457.4 3608.04   551.6 3611.62
#Mann= 5 ,-1,0
       0      .1       0      10     .06       0     160      .1       0
  270.24    .045       0   292.9      .1       0
#XS Ineff= 2 , 0
                          303.35         3607.99
Permanent Ineff=
       F       F
Bank Sta=270.24,292.9
XS Rating Curve= 0 ,0
Exp/Cntr(USF)=0,0
Exp/Cntr=0.3,0.1

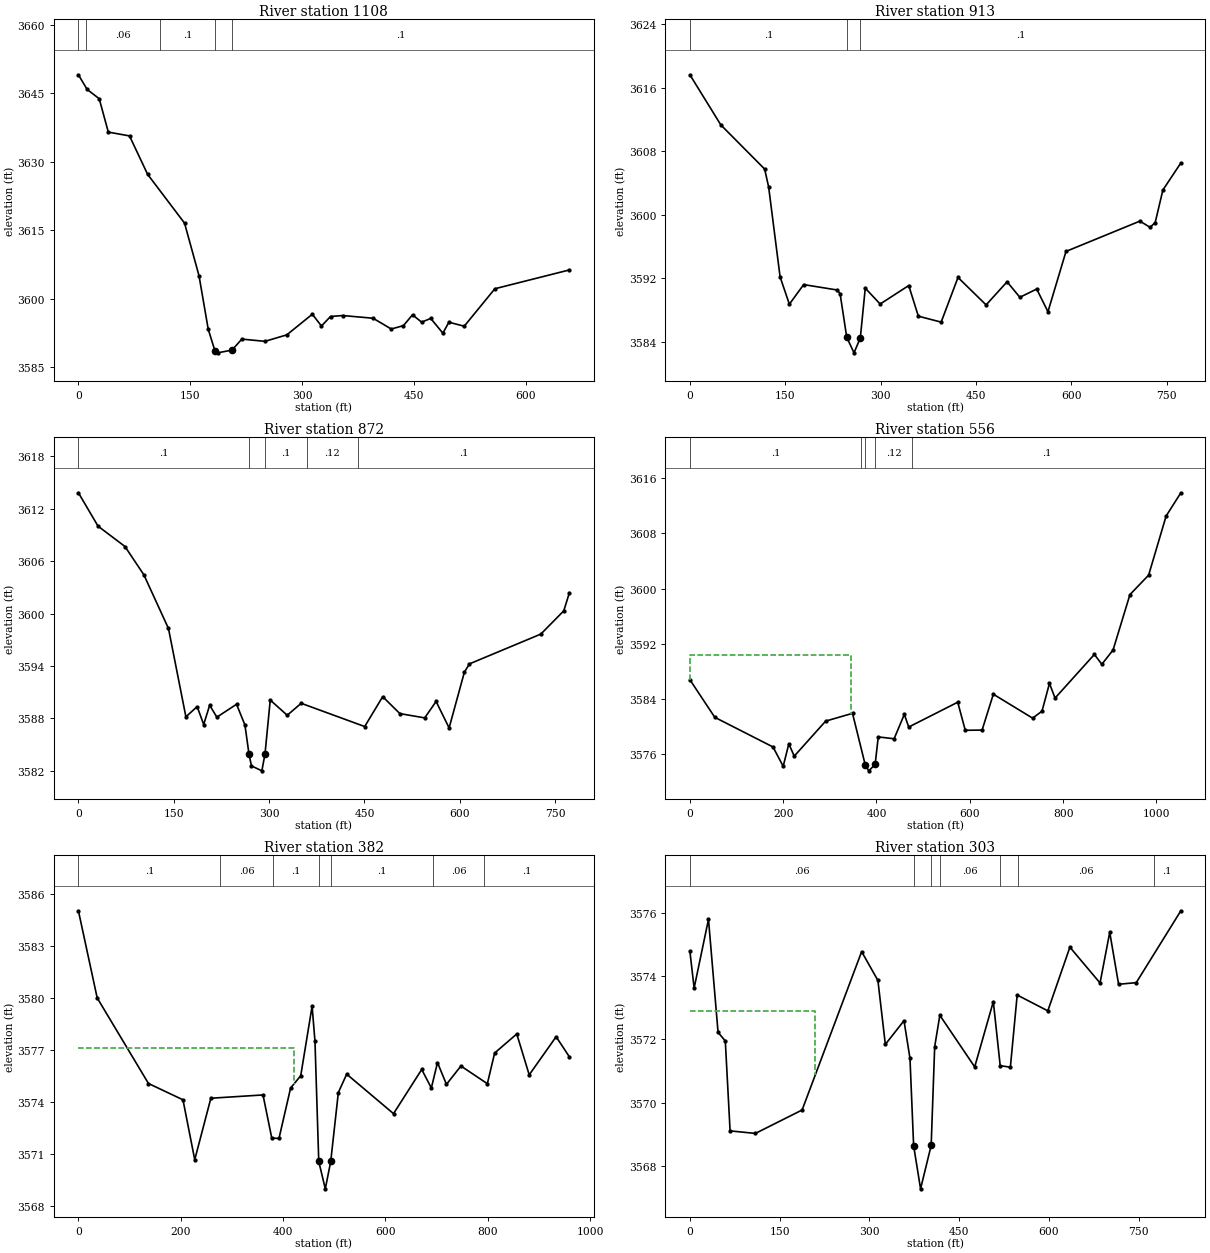
Type RM Length L Ch R = 1 ,1108    ,204.3,195.2,183.2
XS GIS Cut Line= 4
2286972.14102444582881.6245143172286998.19848546583039.186355137
2287019.21956717583132.8024907222287414.86811075583207.079361615
#Sta/Elev= 30
       0  3649.1    11.7 3645.89    27.9 3643.86    40.1 3636.54    68.5 3635.71
    92.8 3627.29   142.3  3616.6   161.7 3605.07     174 3593.39   182.93588.694
   186.5 3588.19   205.93588.786   219.1  3591.2   250.1 3590.71   279.4 3592.13
   313.6 3596.65   325.8 3594.07     338 3596.15   354.3 3596.36     395 3595.77
   419.4 3593.41   435.7 3594.15   447.9 3596.52   460.1 3594.91   472.3 3595.73
   488.6  3592.5   496.7  3594.9   517.2 3594.02   558.3 3602.23   658.2 3606.35
#Mann= 5 ,-1,0
       0      .1       0      10     .06       0     110      .1       0
   182.9    .045       0   205.9      .1       0
Bank Sta=182.9,205.9
XS Rating Curve= 0 ,0
Exp/Cntr(USF)=0,0
Exp/Cntr=0.3,0.1

Type RM Length L Ch R = 1 ,913     ,41.3,41.3,41.5
XS GIS Cut Line= 4
2286783.90296082583023.3508446392286833.65730505583164.084561171
2287211.55926202583342.1993846522287416.46563419583328.363213282
#Sta/Elev= 30
       0 3617.63    48.7 3611.31   117.6 3605.75   123.9 3603.49   141.9 3592.16
   156.5 3588.72     179 3591.19   231.6 3590.51   236.3 3590.05  246.713584.573
  247.22 3584.47   258.2 3582.59  268.123584.473   275.9 3590.74   299.3 3588.74
   344.3 3591.07   359.4 3587.21   395.3 3586.46   421.8 3592.09     466 3588.63
     499 3591.54   519.1 3589.59   545.6 3590.63   563.3 3587.77   591.7 3595.37
     708 3599.19     724  3598.4     732 3599.01   744.1 3603.11   772.4 3606.52
#Mann= 3 ,-1,0
       0      .1       0  247.22    .045       0  268.12      .1       0
Bank Sta=246.71,268.12
XS Rating Curve= 0 ,0
Exp/Cntr(USF)=0,0
Exp/Cntr=0.3,0.1

Type RM Length L Ch R = 1 ,872     ,314.4,316,316.8
XS GIS Cut Line= 4
2286748.42948603583052.0500958112286798.18383026583192.783812343
2287176.08578723583370.898635824 2287380.9921594583357.062464453
#Sta/Elev= 30
       0 3613.83    30.9 3610.01    73.3 3607.68     103 3604.44   141.7  3598.3
   169.1 3588.19   186.8 3589.36   197.1 3587.31   206.5 3589.52   217.8 3588.15
   248.8 3589.63     262 3587.25   268.3 3583.96   272.2 3582.58   288.6 3582.01
  293.57 3583.95   301.8 3590.11   328.5 3588.37   350.5 3589.74   450.4 3587.08
   478.7  3590.5   505.7 3588.56   544.8 3588.07   562.7 3589.95   583.2 3586.92
   607.2  3593.3   615.2 3594.25   727.5 3597.66   763.6 3600.32   772.4 3602.39
#Mann= 5 ,-1,0
       0      .1       0   268.3    .045       0  293.57      .1       0
  359.27     .12       0  439.27      .1       0
Bank Sta=268.3,293.57
XS Rating Curve= 0 ,0
Exp/Cntr(USF)=0,0
Exp/Cntr=0.3,0.1

Type RM Length L Ch R = 1 ,556     ,170.9,173.1,175.2
XS GIS Cut Line= 4
2286601.45327148583232.1782198682286624.61196341583427.359558748
2286884.07773731583588.4196124712287433.00632753583630.152875986
#Sta/Elev= 30
       0 3586.77    53.4 3581.32   178.2 3577.02     200 3574.22   212.1 3577.47
   223.7 3575.69     291 3580.77   348.6  3581.9   375.8 3574.45   383.5 3573.56
   397.1 3574.48   403.8 3578.48   437.8 3578.21   459.7 3581.75   469.1 3579.91
   574.2 3583.51   590.3 3579.44   626.4 3579.47   650.5 3584.67   734.7  3581.2
   754.8 3582.21   770.8 3586.24   782.8 3584.11   867.1 3590.44   883.1 3589.01
   907.2 3591.09   943.3 3599.11   983.4 3601.94  1020.9 3610.51  1052.5 3613.88
#Mann= 5 ,-1,0
       0      .1       0  366.55     .12       0   375.8    .045       0
   397.1     .12       0  476.55      .1       0
#XS Ineff= 2 , 0
          344.98 3590.33
Permanent Ineff=
       F       F
Bank Sta=375.8,397.1
XS Rating Curve= 0 ,0
Exp/Cntr(USF)=0,0
Exp/Cntr=0.3,0.1

Type RM Length L Ch R = 1 ,382     ,79.2,79.4,76.7
XS GIS Cut Line= 6
 2286390.5463501583256.5563371962286383.50921717583403.786217169
2286555.67504323583528.5669534892286719.94335434583694.414767584
2286789.44148596583790.7644500582287033.83165127583754.637165986
#Sta/Elev= 30
       0 3585.06    36.7 3580.03   136.9 3575.09   204.3 3574.15   227.3 3570.69
   258.8 3574.24   360.7 3574.43   377.8 3571.94   391.9 3571.92   414.6 3574.83
   434.4 3575.54   456.6 3579.55   462.2 3577.54  469.62 3570.59   482.4 3569.01
  492.993570.591   507.9 3574.57   524.2 3575.63   615.7 3573.35   670.8  3575.9
   689.6 3574.83   701.6  3576.3   719.1 3575.04   747.4  3576.1     799 3575.08
   813.3 3576.85   856.5 3577.95   880.8 3575.59   933.4 3577.79   959.3 3576.63
#Mann= 7 ,-1,0
       0      .1       0   277.4     .06       0  380.03      .1       0
  469.62    .045       0  492.99      .1       0  693.46     .06       0
  792.26      .1       0
#XS Ineff= 2 , 0
          420.94 3577.12
Permanent Ineff=
       F       F
Bank Sta=469.62,492.99
XS Rating Curve= 0 ,0
Exp/Cntr(USF)=0,0
Exp/Cntr=0.3,0.1

Type RM Length L Ch R = 1 ,303     ,240.7,211.5,217.7
XS GIS Cut Line= 6
2286328.22661247583410.104229135 2286323.4881035583500.135899644
2286494.07442657583580.6905522042286618.85516289583695.994270575
2286749.95391117583855.5240727052286914.22222228583834.990533817
#Sta/Elev= 30
       0 3574.78     7.1 3573.62    31.1 3575.79    47.1 3572.22    59.2 3571.95
    67.2 3569.11   109.5 3569.03   187.6 3569.77   287.1 3574.77   314.3 3573.86
   326.7 3571.84   357.9 3572.59   367.9  3571.4     374 3568.64   385.6 3567.28
   403.3 3568.65   409.2 3571.77   417.8 3572.76   476.1 3571.13   507.2 3573.19
   518.7 3571.17   535.7 3571.12   547.1  3573.4   598.3  3572.9   635.2 3574.91
   685.6 3573.78   701.8 3575.38   716.6 3573.74   746.1 3573.79   820.7 3576.06
#Mann= 7 ,-1,0
       0     .06       0     374    .045       0   403.3      .1       0
  418.81     .06       0   518.7      .1       0   548.7     .06       0
  775.19      .1       0
#XS Ineff= 2 , 0
          209.39 3572.91
Permanent Ineff=
       F       F
Bank Sta=374,403.3
XS Rating Curve= 0 ,0
Exp/Cntr(USF)=0,0
Exp/Cntr=0.3,0.1

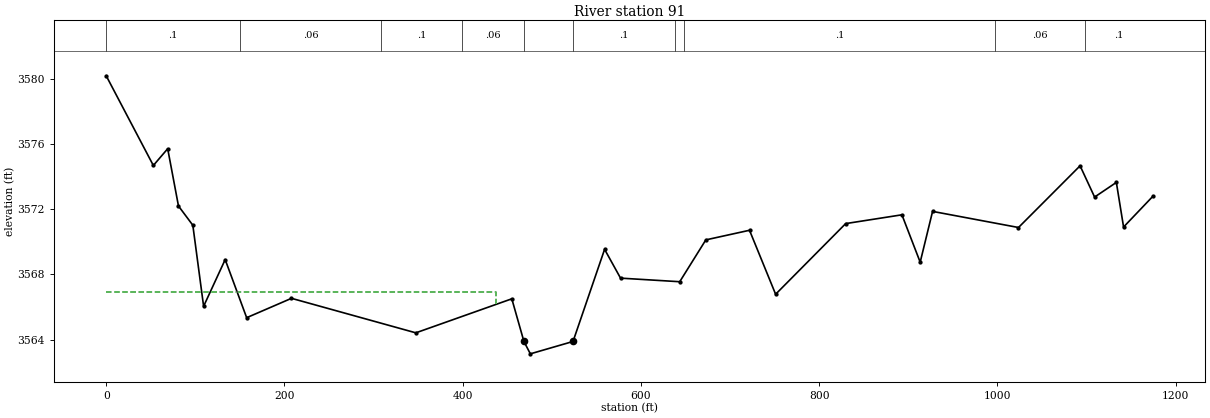
Type RM Length L Ch R = 1 ,91      ,,,
XS GIS Cut Line= 4
2286108.67569667583332.7085825572286088.14215778583500.135899644
2286741.18349442583960.5537401232286944.76387997583923.698670324
#Sta/Elev= 30
       0  3580.2    52.9 3574.69      69 3575.72    81.1  3572.2    97.2 3571.02
   109.3 3566.04   133.5 3568.91   157.6 3565.34   207.9 3566.53   347.4 3564.41
   455.1  3566.5  468.69 3563.88   475.9 3563.12  523.79 3563.88   559.2 3569.54
   577.1 3567.77   643.5 3567.55   672.8 3570.12   721.8 3570.71   751.1 3566.78
   829.7 3571.12   892.8 3571.66   913.3 3568.75   927.2 3571.87  1023.6 3570.88
  1092.7 3574.67    1109 3572.75  1133.4 3573.65  1141.5 3570.91  1174.6 3572.81
#Mann= 10 ,-1,0
       0      .1       0     150     .06       0  308.68      .1       0
  398.68     .06       0  468.69    .045       0  523.79      .1       0
  638.68     .06       0  648.68      .1       0  997.71     .06       0
 1097.71      .1       0
#XS Ineff= 2 , 0
          437.59  3566.9
Permanent Ineff=
       F       F
Bank Sta=468.69,523.79
XS Rating Curve= 0 ,0
Exp/Cntr(USF)=0,0
Exp/Cntr=0.3,0.1
LCMann Table=0

Chan Stop Cuts=-1
Use User Specified Reach Order=0
Composite Channel Slope=5